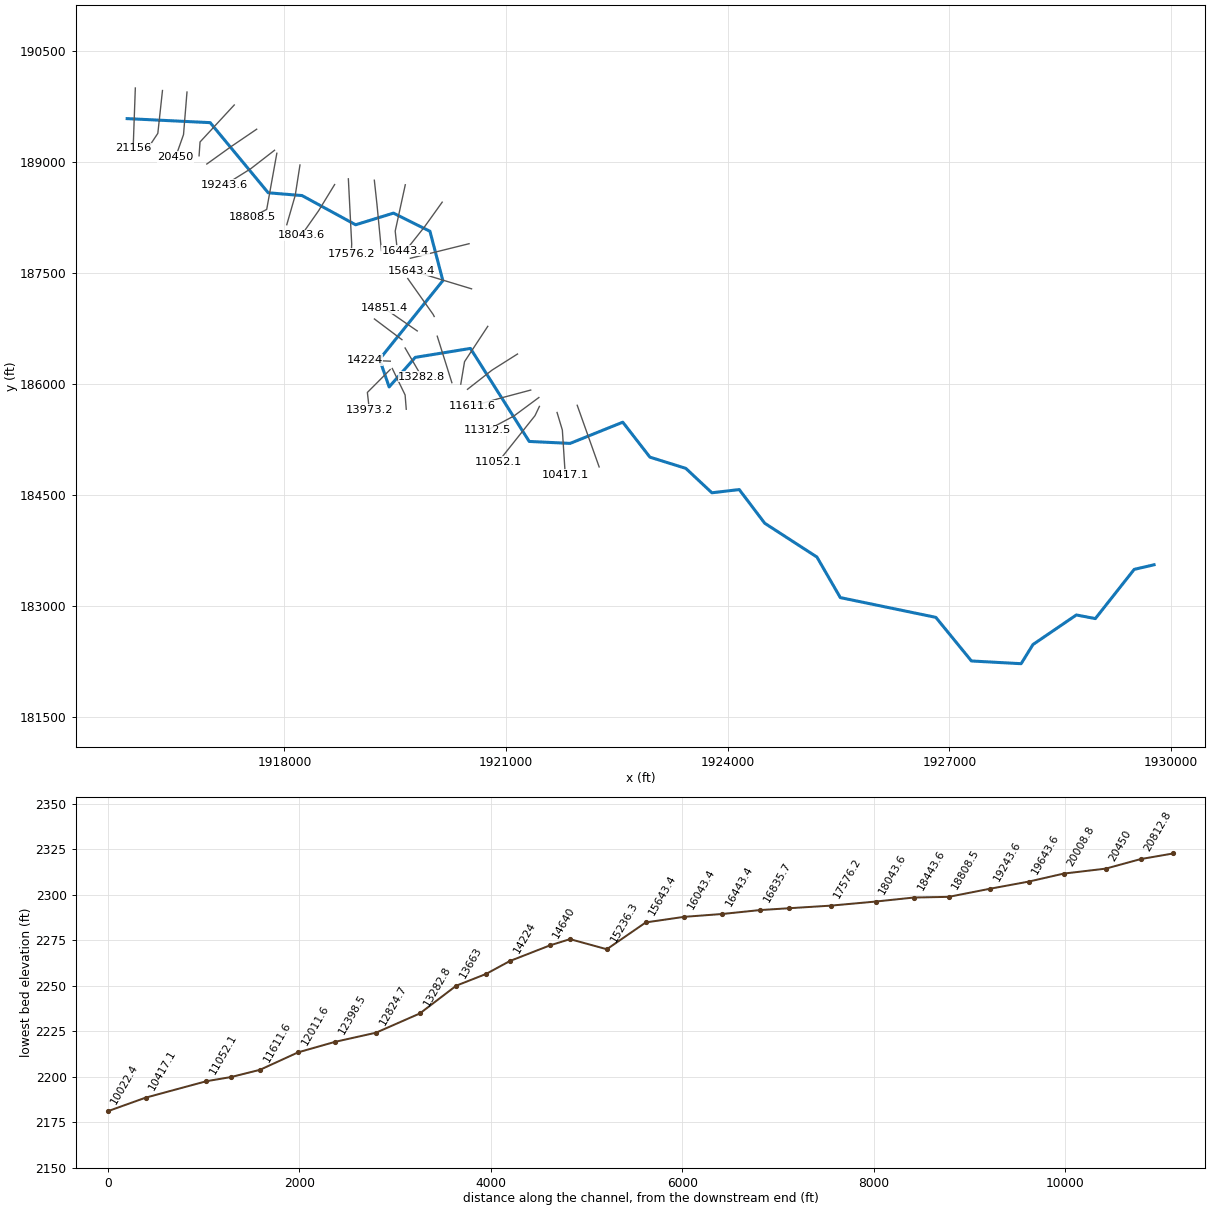
--- MshFrk.prj (project) ---

Proj Title=MshFrk
Current Plan=p01
Default Exp/Contr=0,0
English Units
Geom File=g01
Flow File=f01
Plan File=p01
BEGIN DESCRIPTION:
END DESCRIPTION:
DSS Export Rating Curves= 0
DSS Export Rating Curve Sorted= 0
DSS Export Volume Flow Curves= 0
DXF OffsetX= 0
DXF OffsetY= 0
DXF ScaleX= 0
DXF ScaleY= 0

--- MshFrk.p01 (plan) ---

Plan Title=Floodplain
Program Version=4.00
Geom File=g01
Flow File=f01
K Sum by GR=0
Std Step Tol=0.01
Critical Tol=0.01
Num of Std Step Trials=20
Max Error Tol=0.3
Flow Tol Ratio=0.001
Split Flow NTrial=30
Split Flow Tol=0.02
Split Flow Ratio=0.02
Log Output Level=0
Friction Slope Method=1
Unsteady Friction Slope Method=2
Unsteady Bridges Friction Slope Method=1
Global Log Level=0
CheckData=False
Run HTab=0
Run UNet=0
Run PostProcess=0
UNET Theta=0
UNET Theta Warmup=0
UNET ZTol=0
UNET ZSATol=0
UNET MxIter=0
UNET MaxInSteps=0
UNET DtIC=0
UNET DtMin=0
UNET MaxCRTS=0
UNET WFStab=0
UNET SFStab=0
UNET WFX=0
UNET SFX=0
UNET DSS MLevel=0
UNET DZMax Abort=0
UNET Convert EG Bridges=0
UNET Use Existing IB Tables=0
UNET Froude Limit=0
UNET Froude Power=0
Write IC File=0
Echo Input=False
Echo Output=False
Write Detailed=0

--- MshFrk.f01 (steady flow) ---

Flow Title=NFF Regression Equation
Program Version=4.00
Number of Profiles=1
Profile Names=P100yr
River Rch & RM=MshFrk,Main      ,21156
602.2943
River Rch & RM=MshFrk,Main      ,20450
633.9459
River Rch & RM=MshFrk,Main      ,18808.5
682.6304
River Rch & RM=MshFrk,Main      ,18443.6
762.5409
River Rch & RM=MshFrk,Main      ,17576.2
836.7404
River Rch & RM=MshFrk,Main      ,17138.1
1301.451
River Rch & RM=MshFrk,Main      ,13663
1410.363
River Rch & RM=MshFrk,Main      ,9533.9
1547.164
River Rch & RM=MshFrk,Main      ,5043.2
1637.728
River Rch & RM=MshFrk,Main      ,4778.5
2155.191
River Rch & RM=MshFrk,Main      ,317.9
2238.754
Boundary for River Rch & Prof#=MshFrk,Main      ,1
Up Type=0
Dn Type=3
Dn Slope=0.013033

--- MshFrk.g01 (geometry) ---

Geom Title=USGS 3m DEM
Program Version=4.10

River Reach=MshFrk          ,Main
Reach XY= 30
     1915870.911      189592.152     1916995.006      189537.584
     1917780.163      188589.667     1918238.496      188551.907
     1918963.272      188157.408     1919475.475      188314.928
     1919969.506      188069.299     1920144.248        187402.7
     1919287.752      186339.978     1919417.056      185965.562
     1919769.999      186365.026     1920517.953      186486.153
     1921312.715       185228.99     1921866.527      185202.357
     1922579.422      185489.059     1922947.195      185016.415
     1923432.484        184865.1     1923785.371       184534.98
     1924155.885      184578.332     1924500.956      184123.121
     1925207.246      183666.491     1925523.886      183118.177
     1926816.621      182851.386     1927298.428      182261.837
     1927971.117      182224.931     1928131.725      182484.199
     1928718.731      182883.762     1928975.475      182834.459
     1929501.517      183499.824     1929770.508      183561.934

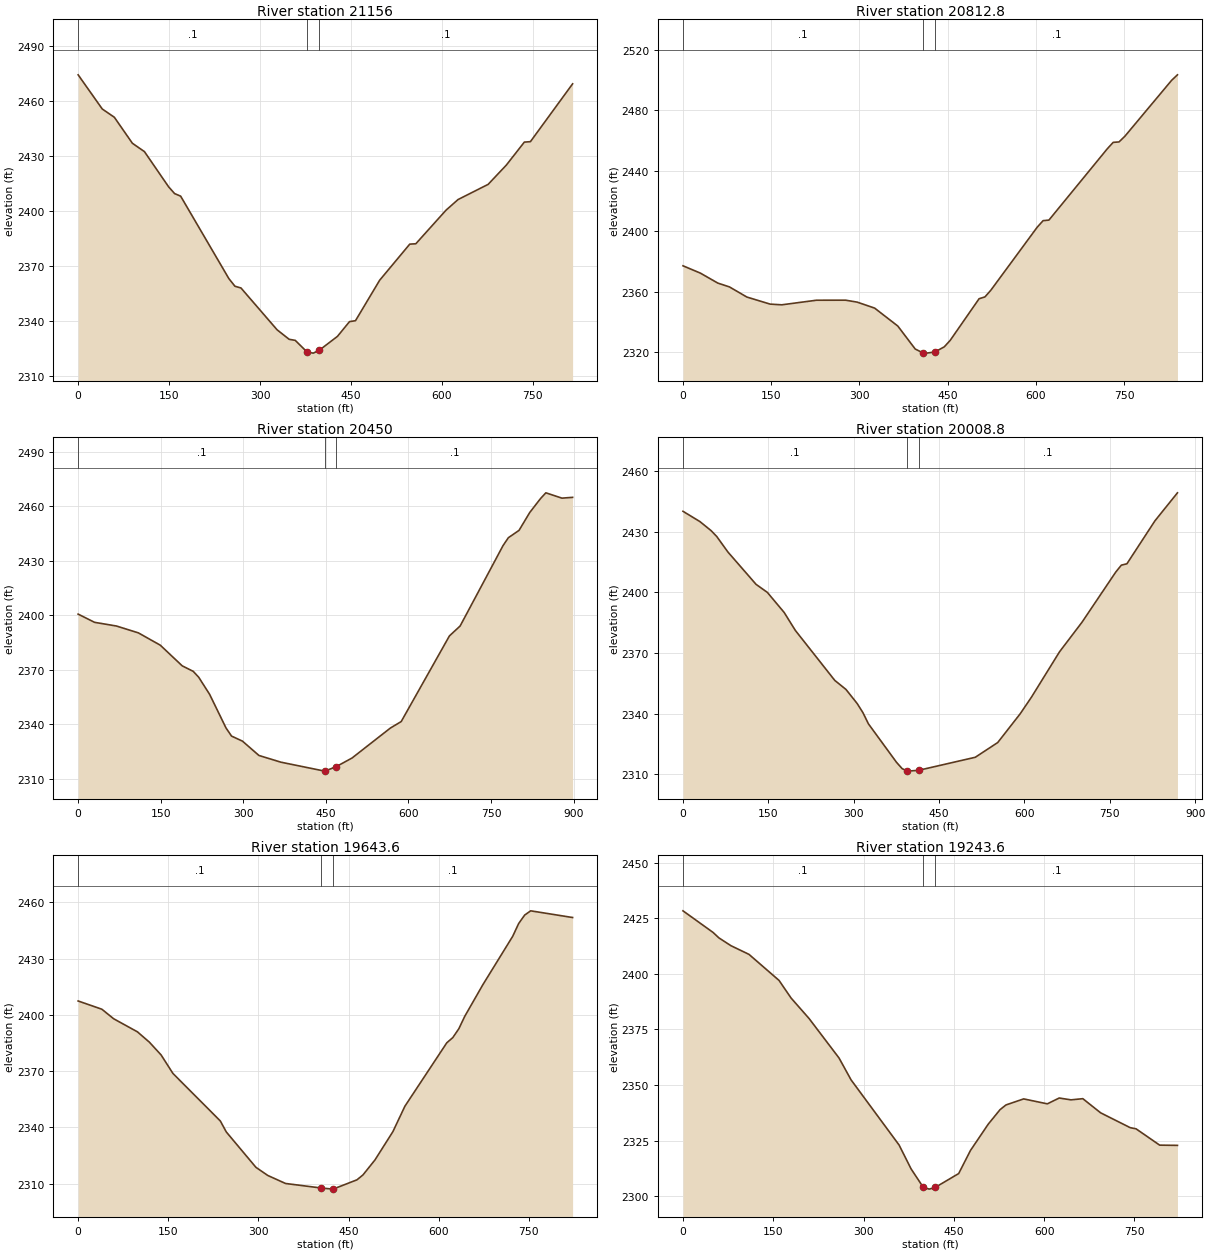
Type RM Length L Ch R = 1 ,21156   ,345,343.2,341.5
XS GIS Cut Line= 2
     1915981.782      190005.764     1915952.358      189190.709
#Sta/Elev= 30
       0 2474.08    39.8 2455.48    59.7 2450.99    89.5 2436.82   109.4 2432.26
   149.2 2413.13   159.1 2409.44   169.1 2408.03   248.6 2363.17   258.6 2359.01
   268.6 2358.05   328.2 2335.27   348.1 2330.11   358.1 2329.54     378 2323.08
   387.9 2322.59   397.8 2324.18   427.7  2331.7   447.6 2339.73   457.5 2340.25
   497.3 2362.25     547 2381.92     557 2382.12   606.7 2400.36   626.6 2406.18
   676.3 2414.46   706.2 2424.91     736 2437.46     746  2437.7   815.6 2469.18
#Mann= 3 , 0 , 0
       0      .1       0     378    .045       0   397.8      .1       0
Bank Sta=378,397.8
XS Rating Curve= 0 ,0
Exp/Cntr=0.3,0.1

Type RM Length L Ch R = 1 ,20812.8 ,362,362.8,363.6
XS GIS Cut Line= 3
      1916349.24      189971.977     1916286.288      189392.992
     1916143.088      189178.084
#Sta/Elev= 30
       0 2377.22    29.6 2372.37    59.2 2365.78      79 2363.25   108.6 2356.55
   148.1 2351.88   167.8 2351.41     227 2354.45   276.4 2354.47   296.1 2353.19
   325.8 2349.24   365.2 2337.37   394.8 2322.17   408.7 2319.48   414.6 2319.46
   428.7  2320.3   444.2 2323.63   454.1 2327.81   503.4 2355.44   513.3 2356.64
   523.2 2360.98   602.3  2402.8   612.2 2407.07   622.1 2407.45   721.4 2454.64
   731.4 2458.85   741.3 2459.14   751.2 2462.89   830.7 2499.89   840.6 2503.52
#Mann= 3 , 0 , 0
       0      .1       0   408.7    .045       0   428.7      .1       0
Bank Sta=408.7,428.7
XS Rating Curve= 0 ,0
Exp/Cntr=0.3,0.1

Type RM Length L Ch R = 1 ,20450   ,458.2,441.1,424.1
XS GIS Cut Line= 3
     1916681.018      189951.253     1916634.026      189376.075
     1916526.885      189073.449
#Sta/Elev= 30
       0 2400.68    29.8 2396.16    69.6 2394.13   109.4 2390.36   149.2 2383.58
     189 2372.21     209 2369.18   218.9 2365.97   238.8 2356.53   268.6 2337.99
   278.6 2333.54   298.5 2330.74   328.4 2322.86   368.2 2319.17   447.8 2314.24
   448.2 2314.26   468.2 2316.62   497.5 2321.46   567.1 2337.95   586.8 2341.53
   674.4  2388.7   693.8 2394.14   771.7 2438.38   781.4 2442.74   800.8 2446.79
   820.3 2456.65   839.8 2464.27   849.5 2467.46   878.7 2464.54   898.1 2464.97
#Mann= 3 , 0 , 0
       0      .1       0   448.2    .045       0   468.2      .1       0
Bank Sta=448.2,468.2
XS Rating Curve= 0 ,0
Exp/Cntr=0.3,0.1

Type RM Length L Ch R = 1 ,20008.8 ,371.2,365.1,359.7
XS GIS Cut Line= 3
     1917320.664      189776.558     1916857.706      189276.453
     1916844.521      189089.508
#Sta/Elev= 30
       0 2440.08    29.6 2435.02    49.4 2430.51    59.3 2427.61      79 2419.91
   128.4 2403.93   148.2 2399.96   177.8 2390.01   197.5  2381.1   266.7  2356.4
   286.4 2351.92   306.2  2344.9   316.1 2340.48   325.9 2334.88   375.3 2315.82
   385.2  2312.7     394 2311.62   395.1 2311.49     414 2311.89   513.6 2318.34
   553.1 2325.64   592.6 2339.89   612.4 2348.12   661.7 2370.55   701.2 2385.19
   760.4 2409.98   770.3 2413.42   780.1 2414.11   829.4 2435.39   868.9 2449.22
#Mann= 3 , 0 , 0
       0      .1       0     394    .045       0     414      .1       0
Bank Sta=394,414
XS Rating Curve= 0 ,0
Exp/Cntr=0.3,0.1

Type RM Length L Ch R = 1 ,19643.6 ,398.4,400,398.3
XS GIS Cut Line= 3
     1917624.268      189448.875     1917281.361      189216.403
     1916949.175      188978.362
#Sta/Elev= 30
       0 2407.43    39.5 2403.03    59.2 2397.93    98.6 2390.99   118.4 2385.52
   138.1 2378.65   157.8 2368.78   236.7 2343.43   246.6 2337.58   295.9 2318.73
   315.6 2314.39   345.2 2310.11   404.3 2307.71   424.2  2307.1   424.3 2307.11
   464.1 2312.06   474.1 2314.68     494 2322.64   523.9 2337.76   543.9 2351.33
   613.6 2385.13   623.6  2387.9   633.6  2392.6   643.5 2399.25   673.4 2415.98
   723.3 2441.91   733.2 2448.71   743.2 2453.23   753.2  2455.5     823 2451.93
#Mann= 3 , 0 , 0
       0      .1       0   404.3    .045       0   424.3      .1       0
Bank Sta=404.3,424.3
XS Rating Curve= 0 ,0
Exp/Cntr=0.3,0.1

Type RM Length L Ch R = 1 ,19243.6 ,416.4,434.8,455.8
XS GIS Cut Line= 3
     1917865.997      189164.339      1917542.71      188913.894
     1917192.511      188695.651
#Sta/Elev= 30
       0 2428.33    49.9 2418.63    59.8 2416.14    79.8 2412.64   109.7 2408.75
   159.6 2397.05   179.5 2389.16   209.5 2379.92   259.3 2362.16   279.3 2352.33
   359.1 2323.04     379 2312.32   398.9 2304.18     409 2303.22   418.9 2303.96
   458.1 2310.22   477.7 2320.61   507.2 2332.42   526.8 2338.94   536.7 2341.07
   566.1 2343.78   605.4 2341.56   625.1 2344.18   644.7 2343.35   664.4 2343.88
   693.9 2337.53     743 2330.86   752.8 2330.33   792.1 2322.99   821.6 2322.89
#Mann= 3 , 0 , 0
       0      .1       0   398.9    .045       0   418.9      .1       0
Bank Sta=398.9,418.9
XS Rating Curve= 0 ,0
Exp/Cntr=0.3,0.1

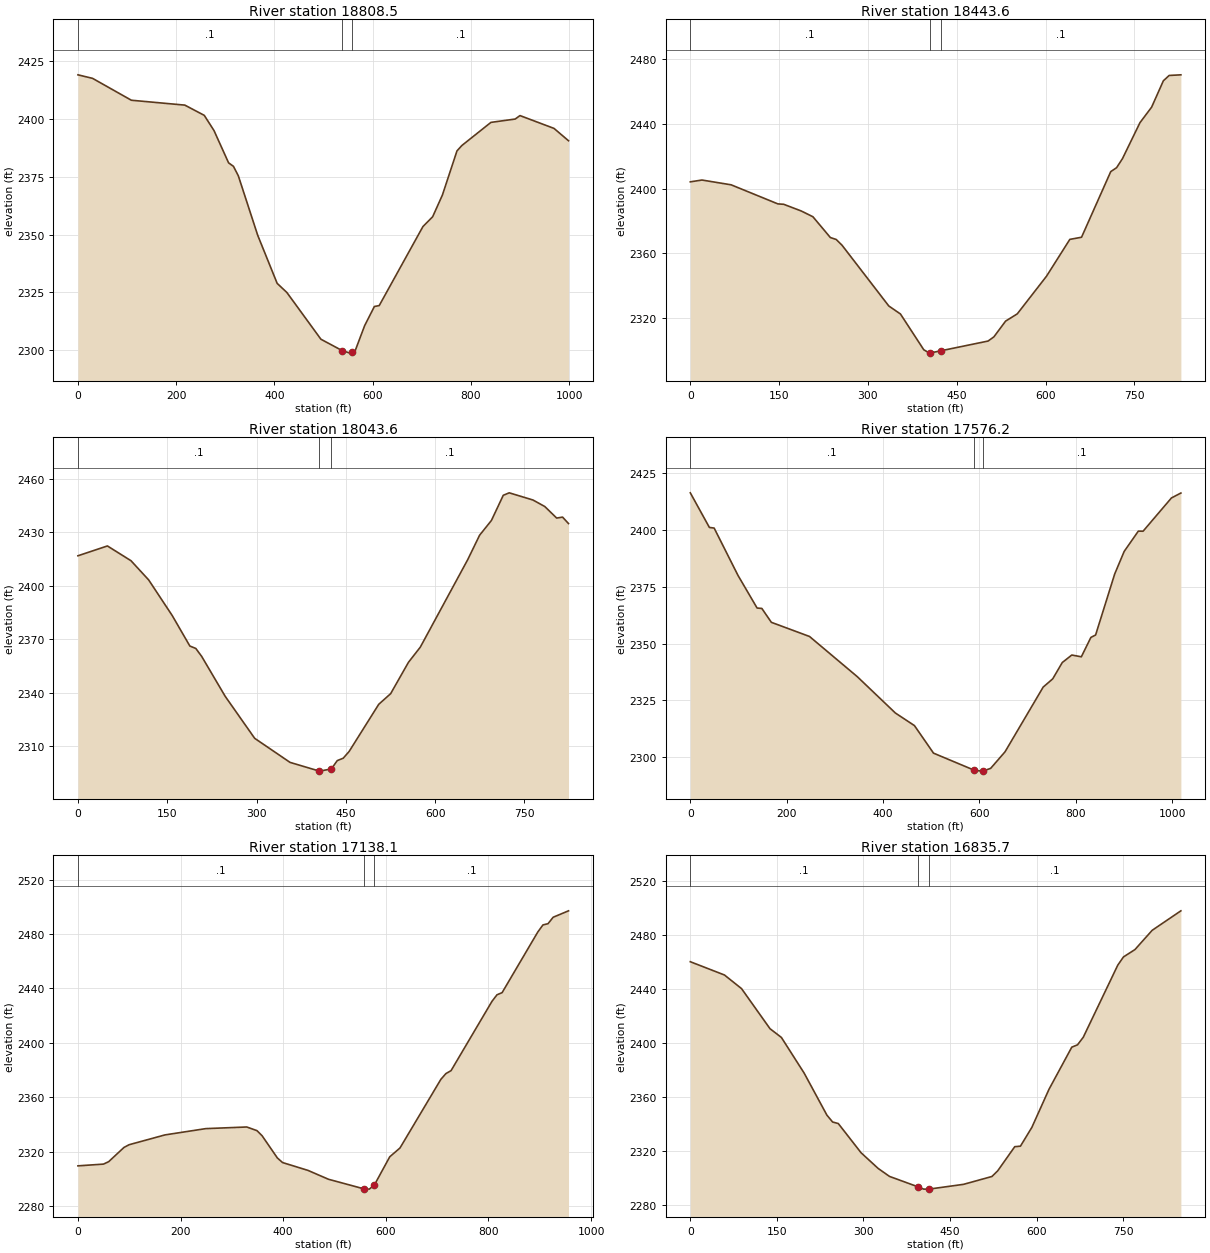
Type RM Length L Ch R = 1 ,18808.5 ,364.4,364.9,362.3
XS GIS Cut Line= 3
     1917897.162        189124.2     1917759.947      188364.814
     1917559.806      188257.519
#Sta/Elev= 30
       0 2419.18    29.7 2417.66   108.8 2408.18   217.6 2406.07   257.2 2401.64
     277 2395.06   306.7 2381.09   316.6 2379.58   326.5  2375.5     366 2349.74
   405.6 2328.92   425.4 2324.97   494.7 2304.74   538.4 2299.78     554 2298.73
   558.4 2299.05   563.9 2299.46   583.7 2310.61   603.5  2318.9   613.4 2319.31
   702.4 2353.51   722.2 2357.76     742 2367.13   771.7 2386.25   781.6 2388.58
   840.8 2398.59   890.2 2400.04     900 2401.54   969.2    2396   998.8 2390.65
#Mann= 3 , 0 , 0
       0      .1       0   538.4    .045       0   558.4      .1       0
Bank Sta=538.4,558.4
XS Rating Curve= 0 ,0
Exp/Cntr=0.3,0.1

Type RM Length L Ch R = 1 ,18443.6 ,410.1,399.9,391.3
XS GIS Cut Line= 3
     1918210.173      188965.424     1918146.311      188556.239
     1918031.598      188157.896
#Sta/Elev= 30
       0 2404.16    19.7 2405.28      69 2402.32   147.9 2390.54   157.8 2390.29
   187.4 2386.16   207.1  2382.6   236.6 2369.75   246.5 2368.55   256.4 2364.96
   335.3 2327.47     355 2322.52   394.4 2300.42   404.1 2298.35   424.1 2299.86
     503 2305.81   512.8 2308.39   532.6 2318.12   552.3  2322.6   601.7 2345.86
   641.1 2368.61   660.9 2369.94   710.2 2410.46   720.1 2412.91     730 2418.48
   759.6 2440.73   779.3 2450.32   799.1 2466.59   808.9 2469.88   828.7 2470.27
#Mann= 3 , 0 , 0
       0      .1       0   404.1    .045       0   424.1      .1       0
Bank Sta=404.1,424.1
XS Rating Curve= 0 ,0
Exp/Cntr=0.3,0.1

Type RM Length L Ch R = 1 ,18043.6 ,452.5,467.7,484.5
XS GIS Cut Line= 3
     1918679.247      188700.801     1918462.075      188346.348
     1918227.039      188012.351
#Sta/Elev= 30
       0 2416.81    49.5 2422.32    89.1 2414.05   118.8 2403.29   158.4 2383.31
     188 2366.24     198 2364.88   207.8 2360.46   247.4 2338.04   296.9 2314.53
   356.3 2301.04   405.7 2296.14   425.7 2297.35   435.6 2302.03   445.6 2303.38
   455.5 2307.13   505.3 2333.58   525.3 2339.55   555.2  2357.1   575.1 2365.61
   654.8 2414.66   674.7 2428.32   694.6 2436.61   714.5 2450.71   724.5 2452.09
   764.3 2448.08   784.3  2444.4   804.2 2437.95   814.1 2438.48   824.1 2434.87
#Mann= 3 , 0 , 0
       0      .1       0   405.7    .045       0   425.7      .1       0
Bank Sta=405.7,425.7
XS Rating Curve= 0 ,0
Exp/Cntr=0.3,0.1

Type RM Length L Ch R = 1 ,17576.2 ,437.4,437.4,435.4
XS GIS Cut Line= 3
     1918865.191      188778.341     1918910.303      187898.657
     1918904.664      187761.441
#Sta/Elev= 30
       0 2416.23    39.6 2401.02    49.5 2400.73      99 2379.92   138.6 2365.59
   148.5 2365.41   168.2 2359.31   247.4 2353.09   346.4 2335.45   425.6 2319.45
   465.2 2313.91   504.8  2301.8   587.8 2294.44   603.7  2293.9   607.8 2293.94
   623.5 2295.14   653.2 2302.39   732.4 2330.84   752.2 2334.46     772 2341.63
   791.8 2344.93   811.6 2344.16   831.4 2352.67   841.2 2353.74   880.8 2380.54
   900.5 2390.47   929.9  2399.4   939.7 2399.35   998.6 2413.98  1018.2 2416.14
#Mann= 3 , 0 , 0
       0      .1       0   587.8    .045       0   607.8      .1       0
Bank Sta=587.8,607.8
XS Rating Curve= 0 ,0
Exp/Cntr=0.3,0.1

Type RM Length L Ch R = 1 ,17138.1 ,309.4,302.4,295.3
XS GIS Cut Line= 3
     1919216.689      188759.544     1919252.402      188432.482
     1919312.552      187808.433
#Sta/Elev= 30
       0 2309.57    49.8 2310.86    59.8 2312.62    89.7  2323.1    99.7  2325.1
   169.5 2332.31   249.2 2336.94     329 2338.13   348.9 2335.45   358.9 2331.68
   388.7 2315.35   398.7 2312.01   448.4 2306.22   488.2 2299.72   557.9 2292.61
   567.8 2292.47   577.8 2295.58   607.6 2316.22   627.6 2322.72   707.2 2373.13
   717.1  2377.4   727.1 2379.54   806.7 2430.39   816.6 2435.29   826.6 2436.88
   896.2 2481.47   906.2 2486.64   916.1 2487.56   926.1 2492.28     956    2497
#Mann= 3 , 0 , 0
       0      .1       0   557.9    .045       0   577.8      .1       0
Bank Sta=557.9,577.8
XS Rating Curve= 0 ,0
Exp/Cntr=0.3,0.1

Type RM Length L Ch R = 1 ,16835.7 ,402.4,392.2,380.7
XS GIS Cut Line= 3
     1919635.654      188698.101     1919499.161      188071.706
     1919522.238      187864.034
#Sta/Elev= 30
       0 2459.94    59.2  2450.1    88.8    2440   138.1 2410.31   157.8 2403.85
   197.3 2377.39   236.7 2346.27   246.6 2341.17   256.4 2340.06   295.9  2318.4
   325.5 2306.78   345.2 2300.86   393.9 2293.27   404.4 2291.46   413.9 2291.49
   473.4    2295   522.7 2300.84   532.6 2305.01   562.2 2322.93     572 2323.28
   591.8 2337.21   621.4 2365.36     661 2396.65   670.9 2398.37   680.9 2404.01
   740.6 2457.35   750.5 2463.48   770.4 2468.94   800.3 2483.23     850 2497.65
#Mann= 3 , 0 , 0
       0      .1       0   393.9    .045       0   413.9      .1       0
Bank Sta=393.9,413.9
XS Rating Curve= 0 ,0
Exp/Cntr=0.3,0.1

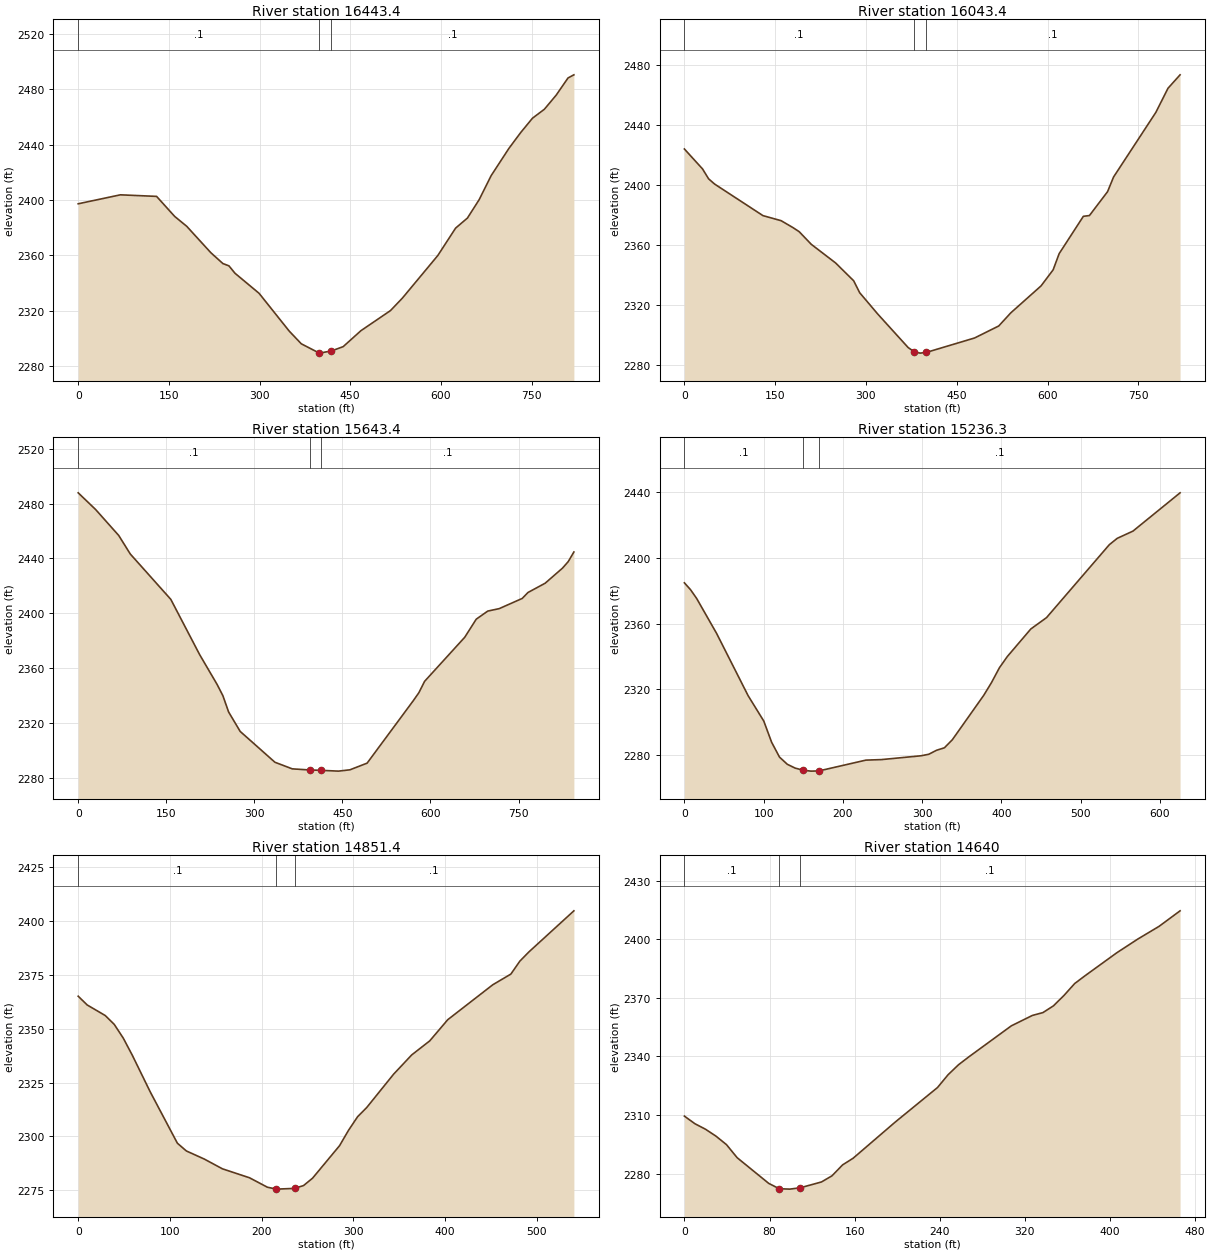
Type RM Length L Ch R = 1 ,16443.4 ,417.6,399.8,383.2
XS GIS Cut Line= 3
     1920135.271      188462.889     1919896.888      188130.492
     1919640.904      187808.816
#Sta/Elev= 30
       0 2397.33    69.8 2403.81   129.7 2402.68   159.6  2388.2   179.6 2381.03
   219.5 2361.93   239.4  2354.1   249.4 2352.44   259.4 2347.09   299.3 2332.57
   349.2 2305.22   369.1 2296.07     399 2289.32     419 2290.89   438.4 2294.01
   467.8 2305.56   516.7  2320.1   536.3 2329.07     595 2359.94   624.4 2379.73
     644 2387.03   663.5  2400.4   683.1  2417.6   712.5 2437.33     732  2448.8
   751.6 2459.23   771.2 2465.67   790.8  2475.9   810.4 2488.33   820.1  2490.6
#Mann= 3 , 0 , 0
       0      .1       0     399    .045       0     419      .1       0
Bank Sta=399,419
XS Rating Curve= 0 ,0
Exp/Cntr=0.3,0.1

Type RM Length L Ch R = 1 ,16043.4 ,413.5,400,386.5
XS GIS Cut Line= 3
      1920499.04      187901.366     1920101.558      187802.885
     1919704.076      187704.403
#Sta/Elev= 30
       0 2423.75      30 2410.47      40 2403.88    49.9  2400.4   129.8 2379.36
   159.8 2375.99   179.8 2371.28   189.8 2368.61   209.7 2360.22   249.7 2347.87
   279.7 2335.95   289.6    2328   319.6 2313.73   369.6  2291.5   379.5 2288.69
   389.5 2287.74   399.5 2288.19   479.4 2297.82   519.4 2305.83   539.3 2314.58
   589.3 2332.54   609.3 2343.26   619.2 2354.02   659.2  2378.9   669.2  2379.4
   699.2 2395.32   709.1 2405.09     779 2448.17     799  2464.2     819 2473.17
#Mann= 3 , 0 , 0
       0      .1       0   379.5    .045       0   399.5      .1       0
Bank Sta=379.5,399.5
XS Rating Curve= 0 ,0
Exp/Cntr=0.3,0.1

Type RM Length L Ch R = 1 ,15643.4 ,423.7,407,390.3
XS GIS Cut Line= 3
     1920532.468      187291.588     1920145.812      187408.879
     1919724.669      187537.276
#Sta/Elev= 30
       0 2487.92    29.6 2475.77      69  2456.8    88.7 2443.26   157.7 2410.14
     207 2369.66   236.5 2348.07   246.4 2339.84   256.2 2327.89   275.9 2313.69
   335.1 2291.17   364.6 2286.35   394.1 2285.54   414.1 2285.26   443.2 2284.69
   462.8 2285.65   492.1 2290.52   570.4 2335.92   580.2 2341.91     590 2350.24
   658.4 2382.45     678 2395.66   697.6 2401.56   717.1 2403.35   756.3 2410.79
   766.1 2415.13   795.4 2421.92   824.8 2432.88   834.6 2437.65   844.3 2444.71
#Mann= 3 , 0 , 0
       0      .1       0   394.1    .045       0   414.1      .1       0
Bank Sta=394.1,414.1
XS Rating Curve= 0 ,0
Exp/Cntr=0.3,0.1

Type RM Length L Ch R = 1 ,15236.3 ,376.2,385,393.8
XS GIS Cut Line= 3
     1920026.913      186917.533     1920013.146      186945.068
     1919669.168      187430.441
#Sta/Elev= 30
       0 2384.82     7.7 2380.66    15.4 2375.35    40.7 2353.92    80.4 2316.02
   100.2  2300.5   110.1 2287.58     120 2278.54   129.9 2274.12   139.8  2271.8
   149.8 2270.52   159.7 2269.95   169.6 2270.05   229.1 2276.66   248.9 2276.99
   298.5  2279.3   308.4 2280.22   318.3 2282.67   328.2 2284.18   338.2 2289.08
   377.8 2316.15   387.7    2324   397.6 2332.98   407.6 2339.83   437.3 2356.67
   457.1 2363.58   536.4 2408.09   546.4 2411.97   566.2 2416.36   625.7 2439.72
#Mann= 3 , 0 , 0
       0      .1       0   149.8    .045       0   169.6      .1       0
Bank Sta=149.8,169.6
XS Rating Curve= 0 ,0
Exp/Cntr=0.3,0.1

Type RM Length L Ch R = 1 ,14851.4 ,212.5,211.5,210.4
XS GIS Cut Line= 2
     1919797.456      186722.494      1919352.35      187028.839
#Sta/Elev= 30
       0 2365.16     9.8 2361.09    29.5 2356.17    39.3 2352.06    49.1  2345.7
      59  2337.7    78.6 2320.63   108.1 2296.85   117.9 2293.24   137.5 2289.46
   157.2 2284.94   186.7 2280.78   206.2 2276.39   216.1  2275.5   235.8 2275.84
   245.6 2277.15   255.4 2280.56   284.9  2295.7   294.7 2302.87   304.6 2309.18
   314.4 2313.38   343.8 2328.92   363.5 2337.86   383.2 2344.41   402.8 2354.24
   451.9 2370.48   471.6 2375.44   481.4 2381.45   491.2 2385.71   540.3 2404.84
#Mann= 3 , 0 , 0
       0      .1       0   216.1    .045       0   235.8      .1       0
Bank Sta=216.1,235.8
XS Rating Curve= 0 ,0
Exp/Cntr=0.3,0.1

Type RM Length L Ch R = 1 ,14640   ,400.6,415.9,431.2
XS GIS Cut Line= 2
      1919590.37      186604.324     1919217.883      186884.167
#Sta/Elev= 30
       0 2309.42     9.9 2305.51    19.8 2302.71    29.7 2299.15    39.6 2294.79
    49.6 2288.11    79.3 2274.95    89.2 2272.22    99.1 2272.02     109 2272.72
   128.9  2275.7   138.8 2278.87   148.7 2284.44   158.6 2287.84   198.2 2306.38
   237.9 2324.05   247.8 2330.58   257.7 2335.74   267.6 2339.86   307.3 2355.65
   327.1 2360.98     337 2362.43   346.9  2365.9   356.9 2371.28   366.8 2377.29
   376.7 2381.35   406.4 2393.06   426.2  2400.1   446.1 2406.58   465.9 2414.55
#Mann= 3 , 0 , 0
       0      .1       0    89.2    .045       0     109      .1       0
Bank Sta=89.2,109
XS Rating Curve= 0 ,0
Exp/Cntr=0.3,0.1

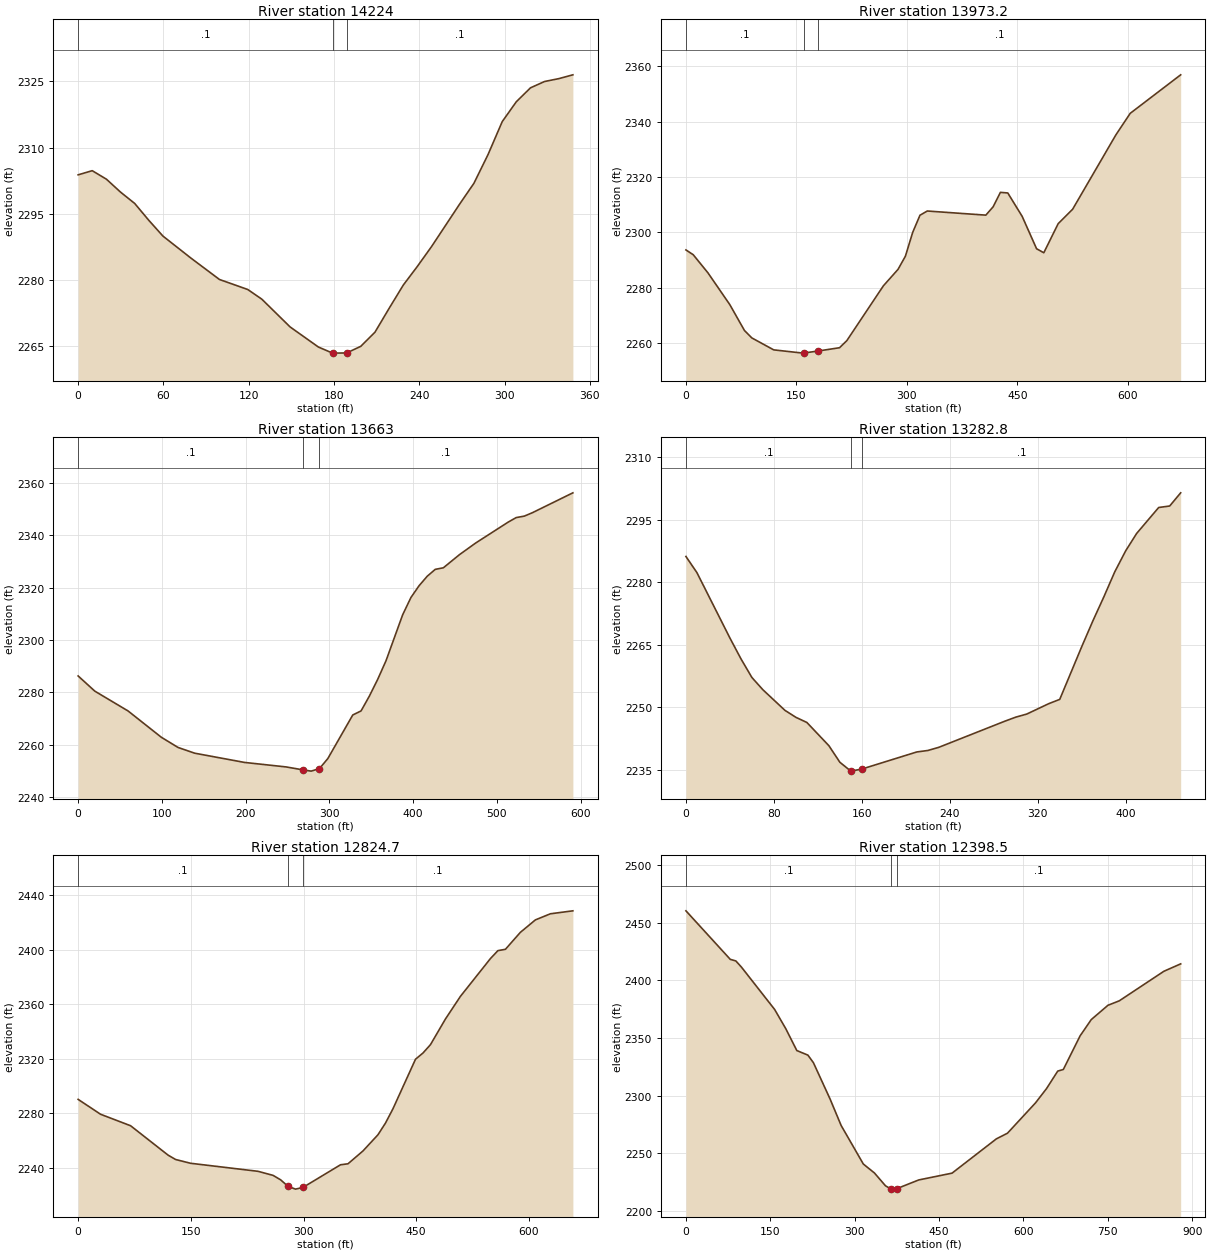
Type RM Length L Ch R = 1 ,14224   ,229.8,250.7,271.6
XS GIS Cut Line= 2
     1919433.096      186313.582     1919085.468       186329.07
#Sta/Elev= 30
       0 2303.86     9.9  2304.8    19.9 2302.87    29.8 2299.95    39.8 2297.37
    49.7 2293.56    59.6    2290    79.5 2284.96    99.4 2280.16   119.3 2277.89
   129.2  2275.7   149.1 2269.41     169 2264.86     179 2263.48   188.9 2263.52
   198.8 2265.02   208.8 2268.23   218.7  2273.6   228.7 2278.89   238.6 2283.12
   248.6 2287.62   268.4 2297.26   278.4 2301.95   288.3 2308.44   298.3 2315.91
   308.2 2320.41   318.2 2323.57   328.1    2325     338 2325.64     348 2326.51
#Mann= 3 , 0 , 0
       0      .1       0     179    .045       0   188.9      .1       0
Bank Sta=179,188.9
XS Rating Curve= 0 ,0
Exp/Cntr=0.3,0.1

Type RM Length L Ch R = 1 ,13973.2 ,279,310.1,341.2
XS GIS Cut Line= 3
     1919431.375         186200.     1919122.468      185891.093
     1919149.142      185657.906
#Sta/Elev= 30
       0 2293.61     9.9 2291.88    29.8 2285.36    59.6 2273.84    79.4 2264.53
    89.4 2261.84   119.1 2257.52   158.9 2256.34   159.6 2256.36   179.6 2257.11
   208.5 2258.29   218.4 2260.85   268.1 2280.67   287.9 2286.59   297.9 2291.34
   307.8 2299.94   317.7 2306.14   327.6 2307.67   407.1 2306.18     417 2309.19
   426.9 2314.41   436.9 2314.19   456.4 2305.75     476 2294.04   485.8 2292.59
   505.3  2303.1   524.9  2308.3   583.6 2335.15   603.1 2342.95   671.6 2356.86
#Mann= 3 , 0 , 0
       0      .1       0   159.6    .045       0   179.6      .1       0
Bank Sta=159.6,179.6
XS Rating Curve= 0 ,0
Exp/Cntr=0.3,0.1

Type RM Length L Ch R = 1 ,13663   ,379.5,380.2,382
XS GIS Cut Line= 3
      1919459.77      186214.628     1919633.298      185856.961
     1919648.786      185664.216
#Sta/Elev= 30
       0 2286.29    19.9 2280.49    59.6 2272.92    99.4 2262.85   119.3 2258.97
   139.1 2256.78   198.8 2253.24   248.5 2251.52   268.3 2250.41   278.3 2249.92
   288.2 2250.89   298.2 2254.71     328 2271.38   337.9 2272.93   347.8 2278.58
   357.8 2285.01   367.7 2292.11   387.6 2309.68   397.5 2316.29   407.2 2320.78
   416.9 2324.39   426.5 2327.03   436.2 2327.63   455.6 2332.69   474.9 2337.12
   513.6 2345.08   523.2 2346.82   532.9 2347.38   542.6 2348.69   590.9 2356.28
#Mann= 3 , 0 , 0
       0      .1       0   268.3    .045       0   288.2      .1       0
Bank Sta=268.3,288.2
XS Rating Curve= 0 ,0
Exp/Cntr=0.3,0.1

Type RM Length L Ch R = 1 ,13282.8 ,462.4,457.7,451.9
XS GIS Cut Line= 2
     1919633.298      186491.985     1919859.409      186102.959
#Sta/Elev= 30
       0 2286.16      10 2282.28      40  2266.6      50 2261.63      60 2257.13
      70 2254.19      90 2249.26     100 2247.58     110 2246.34     130 2240.78
     140  2236.8     150 2234.67     160 2235.17     210 2239.27     220 2239.62
     230 2240.38     290 2246.64     300 2247.62     310 2248.36     330 2250.85
     340 2251.88     360 2264.52     370 2270.63     380  2276.4     390 2282.45
     400 2287.53     410  2291.7     430 2297.91     440 2298.27     450 2301.43
#Mann= 3 , 0 , 0
       0      .1       0     150    .045       0     160      .1       0
Bank Sta=150,160
XS Rating Curve= 0 ,0
Exp/Cntr=0.3,0.1

Type RM Length L Ch R = 1 ,12824.7 ,449.1,426.2,403.2
XS GIS Cut Line= 2
     1920068.216      186651.362     1920266.101      186023.313
#Sta/Elev= 30
       0 2290.06    29.9 2279.11    69.8 2270.69   119.7 2249.09   129.7 2245.88
   149.7  2243.1   239.4  2237.2   259.4 2234.23   269.4 2230.99   279.2 2226.22
   289.3 2224.11   299.2 2225.35   349.2    2242   359.2 2242.74   379.1 2252.16
   399.1 2264.08   409.1 2272.68     419 2283.13     449 2319.54     459 2324.14
   468.9 2330.24   488.9 2349.15   508.8 2365.75   548.7 2393.48   558.7 2399.36
   568.7 2400.33   588.6 2412.79   608.6 2421.95   628.6 2426.44   658.5 2428.61
#Mann= 3 , 0 , 0
       0      .1       0   279.2    .045       0   299.2      .1       0
Bank Sta=279.2,299.2
XS Rating Curve= 0 ,0
Exp/Cntr=0.3,0.1

Type RM Length L Ch R = 1 ,12398.5 ,398,386.8,378.2
XS GIS Cut Line= 3
        1920752.      186784.448     1920437.643      186307.176
     1920386.741      186003.564
#Sta/Elev= 30
       0 2460.13    78.8  2418.1    88.7 2416.73    98.5 2411.48   157.6 2374.75
   177.4 2358.11   197.1 2339.12   216.8 2335.14   226.6 2328.59   256.2 2297.16
   275.9 2274.19   315.3 2240.85     335 2233.11   354.7 2221.99   364.6  2219.1
   374.4 2219.44   413.8 2227.05     473 2232.94   551.8 2262.64   571.5 2267.52
   621.2  2293.7     641  2306.2   660.9 2321.34   670.8  2322.7   700.6 2351.83
   720.5 2365.95   750.2 2378.34   770.1 2382.14   849.6 2407.78   879.4  2414.2
#Mann= 3 , 0 , 0
       0      .1       0   364.6    .045       0   374.4      .1       0
Bank Sta=364.6,374.4
XS Rating Curve= 0 ,0
Exp/Cntr=0.3,0.1

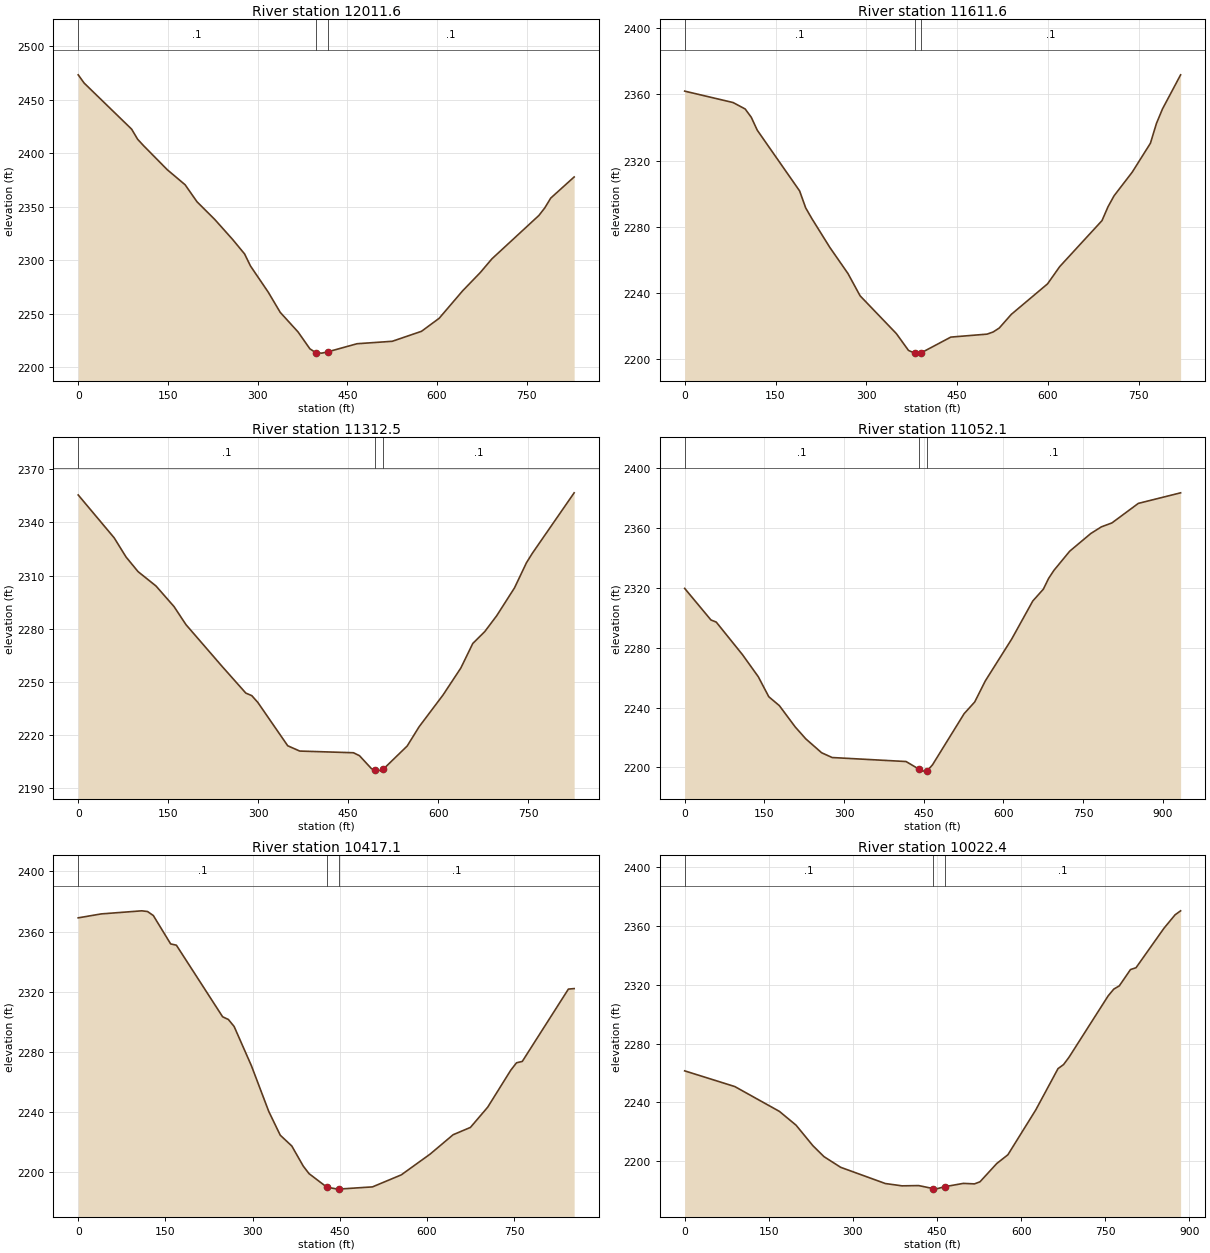
Type RM Length L Ch R = 1 ,12011.6 ,407.6,400,390.2
XS GIS Cut Line= 3
     1921154.362      186410.448     1920809.951      186193.045
     1920477.322      185933.285
#Sta/Elev= 30
       0 2473.26     9.9 2465.56    89.4 2422.48    99.3 2413.13   109.3 2407.09
     149 2384.59   178.8 2370.56   198.7 2354.66   228.5 2338.08   258.3 2319.44
   278.2 2305.98   288.1  2294.7   317.9 2270.16   337.8 2251.42   367.6 2233.12
   387.4 2217.36   397.3 2213.76   407.3 2213.33   417.3 2214.53   466.2  2222.1
   525.1 2224.38   574.1 2233.72   603.6 2245.88   642.8  2271.5   672.3 2288.56
   691.9 2301.45   770.4 2341.94   780.2 2348.98   790.1  2358.1   829.3 2377.86
#Mann= 3 , 0 , 0
       0      .1       0   397.3    .045       0   417.3      .1       0
Bank Sta=397.3,417.3
XS Rating Curve= 0 ,0
Exp/Cntr=0.3,0.1

Type RM Length L Ch R = 1 ,11611.6 ,293.2,299,304.4
XS GIS Cut Line= 3
     1921333.143      185923.219     1920937.342      185817.989
     1920543.145       185707.12
#Sta/Elev= 30
       0 2362.01    79.9 2355.12    99.9 2351.22   109.9 2346.25   119.9 2338.38
   189.8 2301.72   199.8  2291.5   209.8 2285.13   239.7 2267.59   269.7 2251.77
   289.7 2238.33   349.6 2215.49   369.6 2205.34   379.6 2203.71   389.6  2203.7
   439.5 2213.38   499.4 2215.18   509.4 2216.48   519.4 2218.83   539.4 2227.12
   599.3 2245.57   619.3 2255.97   689.2 2283.78   699.2 2292.22   709.2 2298.82
   739.1 2313.06   769.1  2330.5   779.1 2342.51   789.1 2351.29     819 2371.86
#Mann= 3 , 0 , 0
       0      .1       0   379.6    .045       0   389.6      .1       0
Bank Sta=379.6,389.6
XS Rating Curve= 0 ,0
Exp/Cntr=0.3,0.1

Type RM Length L Ch R = 1 ,11312.5 ,250.1,260.3,270.6
XS GIS Cut Line= 3
     1921443.676      185822.524     1921106.537      185573.446
     1920747.008      185381.274
#Sta/Elev= 30
       0 2355.43    59.9 2331.29    79.8 2320.44    99.8 2312.21   129.7 2304.11
   159.7 2292.54   179.6 2282.36   239.5 2258.95   279.4 2243.76   289.4 2242.31
   299.4 2238.52   349.3 2214.06   369.3 2211.08   458.9 2210.13   468.9 2208.47
   488.8  2201.2   495.5 2200.23   498.7 2199.77   508.7  2200.9   548.4 2213.91
   568.3 2224.77   608.1 2242.63   637.9  2257.9   657.8 2271.72   677.7 2278.38
   697.6 2287.32   727.4 2303.08   747.3 2317.23   757.2  2322.6   826.8 2356.63
#Mann= 3 , 0 , 0
       0      .1       0   495.5    .045       0   508.7      .1       0
Bank Sta=495.5,508.7
XS Rating Curve= 0 ,0
Exp/Cntr=0.3,0.1

Type RM Length L Ch R = 1 ,11052.1 ,616.1,634.9,653.8
XS GIS Cut Line= 3
     1921451.029      185702.589     1921391.422        185577.5
     1920895.793       184955.67
#Sta/Elev= 30
       0 2319.74    49.5  2298.6    59.4 2297.22   108.9 2275.36   138.6 2260.63
   158.4 2247.23   178.3 2241.27   208.1 2227.04     228 2219.06   257.8 2209.76
   277.7 2206.55   416.9 2203.87   441.7 2198.63   446.7 2197.45   456.6 2197.69
   466.6 2201.65   526.2 2235.91   546.1 2243.73     566  2257.8   615.7 2285.82
   655.4 2311.29   675.3 2319.21   685.3 2326.46   695.2 2331.79     725 2344.66
   764.8 2356.51   784.6 2360.94   804.5 2363.57   854.2 2376.64   933.8 2383.71
#Mann= 3 , 0 , 0
       0      .1       0   441.7    .045       0   456.6      .1       0
Bank Sta=441.7,456.6
XS Rating Curve= 0 ,0
Exp/Cntr=0.3,0.1

Type RM Length L Ch R = 1 ,10417.1 ,383.5,394.5,403.2
XS GIS Cut Line= 3
     1921690.046      185620.318     1921761.614      185382.461
     1921800.621      184778.988
#Sta/Elev= 30
       0  2369.1    39.7 2371.73   109.3 2373.78   119.2 2373.33   129.2 2370.64
     159 2351.75   168.9 2350.89   248.4 2303.21   258.3 2301.41   268.2 2296.75
     298 2270.54   327.7 2240.23   347.5 2224.35   367.4 2217.14   387.2  2203.7
   397.1 2198.71   427.8 2189.68   446.7 2188.41   447.8 2188.43   506.2  2189.9
   555.7  2197.9   605.3 2211.72   644.9 2224.64   674.7 2229.52   704.4    2243
   744.1 2267.64     754 2272.57   763.9 2273.48   843.2 2321.65   853.1 2321.98
#Mann= 3 , 0 , 0
       0      .1       0   427.8    .045       0   447.8      .1       0
Bank Sta=427.8,447.8
XS Rating Curve= 0 ,0
Exp/Cntr=0.3,0.1

Type RM Length L Ch R = 1 ,10022.4 ,507.2,488.1,471.4
XS GIS Cut Line= 2
     1921962.729      185717.526     1922259.537      184884.538
#Sta/Elev= 30
       0 2261.41    89.4 2250.73   168.9 2233.85   198.7 2224.43   228.5 2210.56
   248.4 2203.06   278.2  2195.8   357.7 2184.79   387.5  2183.2   417.3 2183.38
   443.6  2181.3   447.1 2180.97   463.6 2182.61   496.8 2184.87   516.7 2184.54
   526.6 2185.96   556.4 2198.36   576.3 2204.33     626 2234.83   665.7 2262.92
   675.6 2265.69   685.6 2270.84   755.1 2312.41   765.1    2317     775 2319.22
   794.9  2330.3   804.8 2331.56   854.5 2358.34   874.4 2367.53   884.3 2370.25
#Mann= 3 , 0 , 0
       0      .1       0   443.6    .045       0   463.6      .1       0
Bank Sta=443.6,463.6
XS Rating Curve= 0 ,0
Exp/Cntr=0.3,0.1