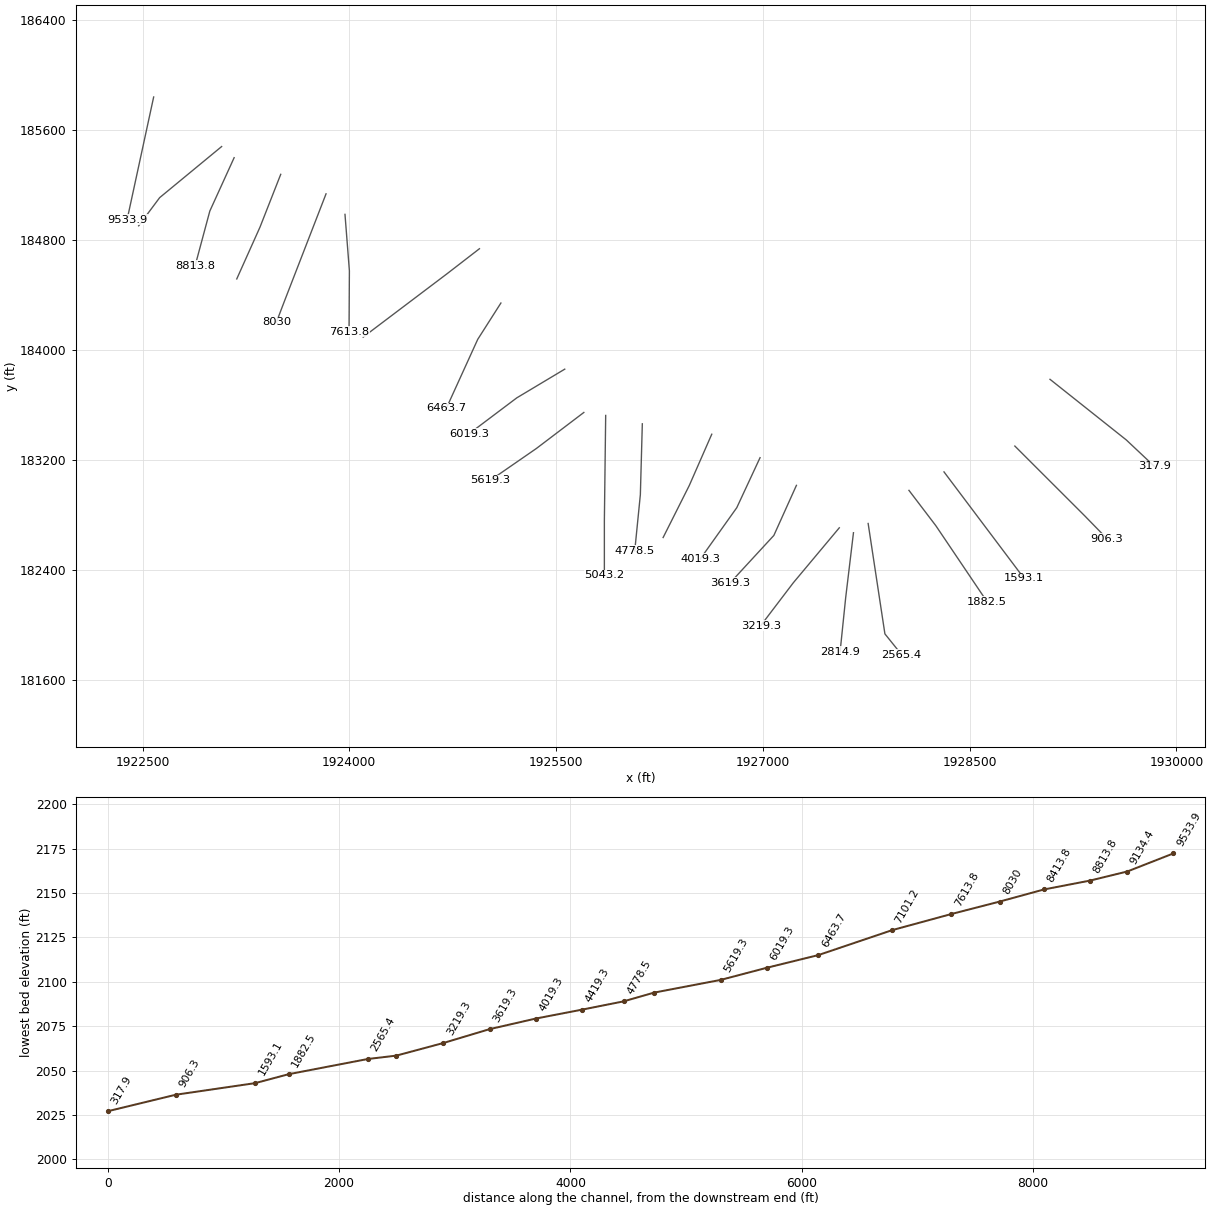
HEC-RAS study MshFrk.prj: MshFrk

--- MshFrk.g01 (geometry) --- (continued)

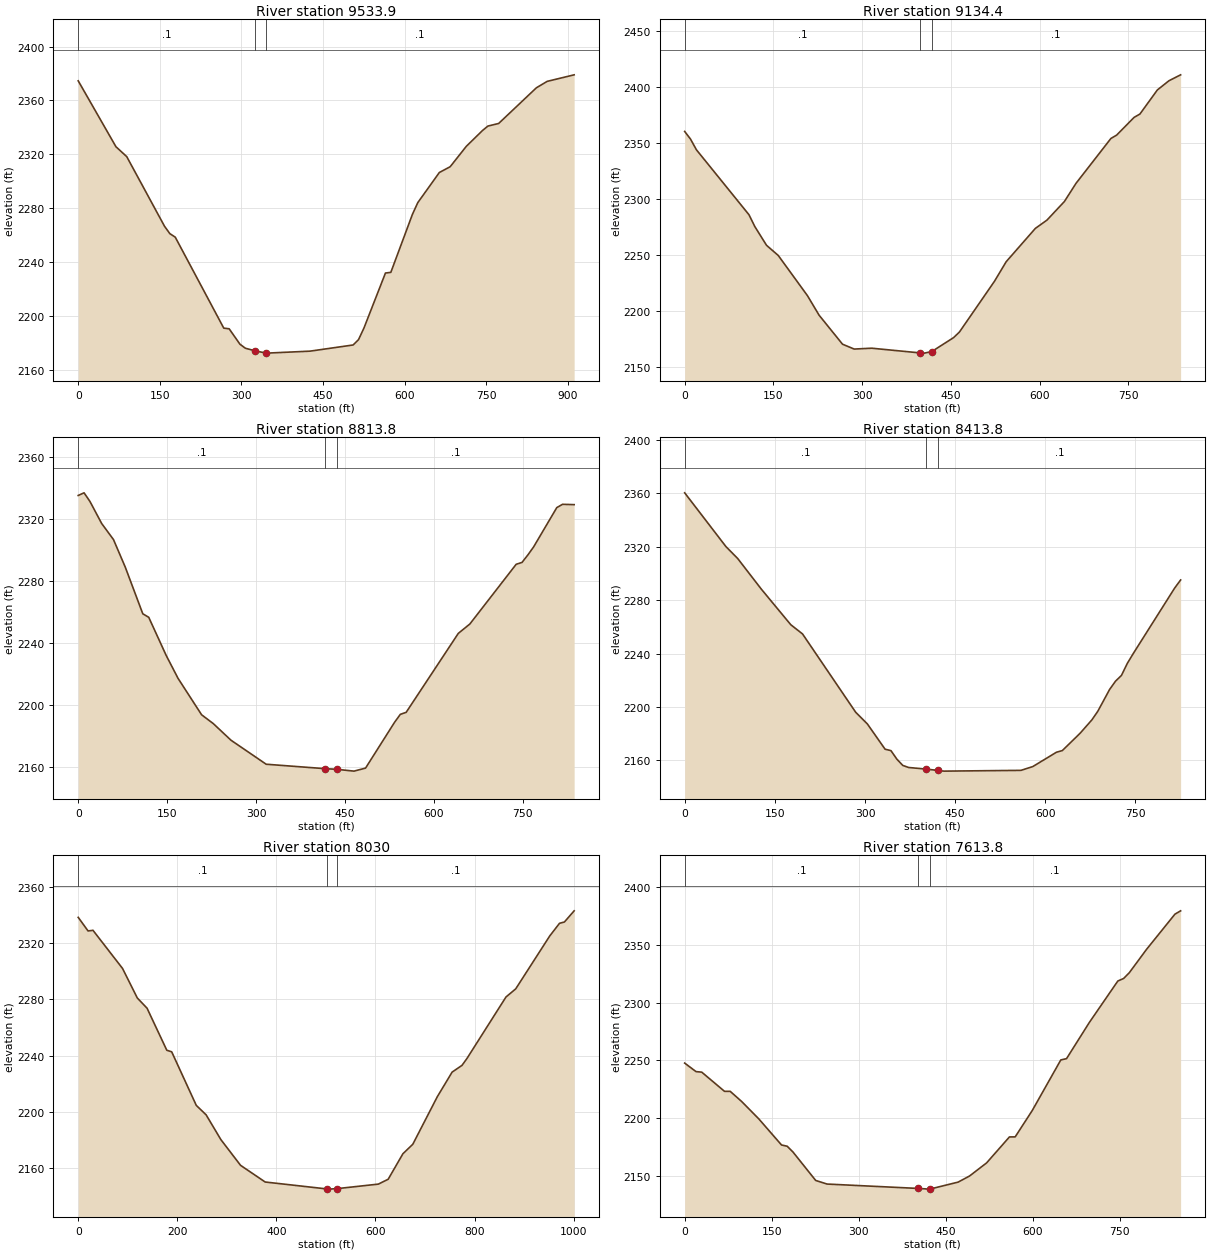
Type RM Length L Ch R = 1 ,9533.9  ,416.3,399.4,382.6
XS GIS Cut Line= 2
     1922580.778      185841.377     1922388.345      184950.257
#Sta/Elev= 30
       0 2374.55    69.4  2325.6    89.2 2318.27   158.6 2266.61   168.5 2261.05
   178.4 2258.46   267.6 2190.89   277.5  2190.4   297.3 2178.99   307.2 2175.99
   325.4 2174.02   345.4 2172.38   346.8 2172.34   426.1  2173.8   505.4 2178.39
   515.3 2182.36   525.2 2190.88   564.8 2231.81   574.7 2232.32   614.4  2275.4
   624.3 2284.12   663.9 2306.48   683.8 2310.77   713.5 2325.93   743.2 2337.64
   753.1 2340.95   772.9 2342.88   842.3 2369.38   862.1 2374.15   911.7 2379.01
#Mann= 3 , 0 , 0
       0      .1       0   325.4    .045       0   345.4      .1       0
Bank Sta=325.4,345.4
XS Rating Curve= 0 ,0
Exp/Cntr=0.3,0.1

Type RM Length L Ch R = 1 ,9134.4  ,308.4,320.6,337
XS GIS Cut Line= 3
     1923073.874      185480.948     1922624.375      185109.407
     1922471.944      184904.457
#Sta/Elev= 30
       0 2360.41     9.9 2353.55    19.8 2344.05   108.7 2285.94   118.6 2275.36
   138.4 2258.59   158.2 2249.52   207.6 2213.55   227.3 2196.07   266.9 2170.13
   286.6 2165.79   316.3 2166.55   397.7 2162.36   405.3 2162.15   417.7 2163.51
   454.7 2176.02   464.6 2181.02   523.9 2226.44   543.6 2243.88     593 2273.71
   612.6 2281.11   642.1 2297.76   661.8 2314.06   720.7 2354.11   730.5 2357.17
     760 2373.02   769.8 2375.98   799.3 2397.54     819 2405.79   838.6 2411.05
#Mann= 3 , 0 , 0
       0      .1       0   397.7    .045       0   417.7      .1       0
Bank Sta=397.7,417.7
XS Rating Curve= 0 ,0
Exp/Cntr=0.3,0.1

Type RM Length L Ch R = 1 ,8813.8  ,398.4,399.6,395.4
XS GIS Cut Line= 3
     1923164.579      185399.864     1922988.224       185011.77
     1922881.895      184615.169
#Sta/Elev= 30
       0 2335.41     9.9 2337.11    19.8 2331.54    39.6 2317.26    59.5 2306.88
    79.3 2289.14     109 2258.84     119 2256.58   148.7 2231.72   168.5 2217.06
   208.2 2193.52     228 2187.78   257.8 2177.05   317.2 2161.51   416.3 2158.65
   436.3 2158.22   465.4 2157.05   484.9 2159.01   533.8 2188.61   543.6 2193.79
   553.4 2195.08   641.4 2246.16   660.9 2252.24   739.1 2290.89   748.9 2292.08
   758.7 2296.87   768.5 2302.12   807.6 2327.54   817.3 2329.68   836.9 2329.46
#Mann= 3 , 0 , 0
       0      .1       0   416.3    .045       0   436.3      .1       0
Bank Sta=416.3,436.3
XS Rating Curve= 0 ,0
Exp/Cntr=0.3,0.1

Type RM Length L Ch R = 1 ,8413.8  ,383.4,384,385.8
XS GIS Cut Line= 3
     1923502.589       185278.74     1923352.368      184895.263
     1923183.645      184518.065
#Sta/Elev= 30
       0 2360.29    68.6 2320.08    88.2 2311.14   127.5 2288.23   176.5 2261.61
   196.1 2254.68   284.4 2196.16     304 2187.32   333.4 2168.45   343.2 2167.35
     353 2161.01   362.8 2156.32   372.6 2154.75   401.9 2153.54   421.9 2152.52
   431.5 2152.03   559.4  2152.6   579.1 2155.42   618.5 2166.16   628.3 2167.41
   657.8 2180.33   677.5 2190.39   687.3  2196.8     707 2213.17   716.8 2219.34
   726.7 2223.67   736.5 2232.73   746.4 2240.08   815.2 2289.03   825.1 2295.07
#Mann= 3 , 0 , 0
       0      .1       0   401.9    .045       0   421.9      .1       0
Bank Sta=401.9,421.9
XS Rating Curve= 0 ,0
Exp/Cntr=0.3,0.1

Type RM Length L Ch R = 1 ,8030    ,405.4,416.2,423.4
XS GIS Cut Line= 3
     1923831.322      185136.942     1923537.616      184377.437
     1923471.074      184203.049
#Sta/Elev= 30
       0 2338.27    19.9 2328.61    29.8 2329.07    89.4    2302   119.2 2281.03
     139  2273.7   178.8 2243.87   188.7 2242.73   238.3  2204.7   258.2 2197.96
     288 2180.35   327.7 2162.09   377.4 2150.24   502.8 2145.29   506.5 2145.19
   522.8 2145.55   605.8 2148.75   625.6 2152.19   655.4 2170.33   675.3 2177.04
   724.9  2210.9   754.7 2228.32   774.6 2233.11   784.5 2237.93   863.4 2281.68
   883.1 2287.48   951.8 2325.09   971.5 2334.06   981.3 2334.96    1001 2342.91
#Mann= 3 , 0 , 0
       0      .1       0   502.8    .045       0   522.8      .1       0
Bank Sta=502.8,522.8
XS Rating Curve= 0 ,0
Exp/Cntr=0.3,0.1

Type RM Length L Ch R = 1 ,7613.8  ,538.3,512.5,490.4
XS GIS Cut Line= 3
     1923968.814      184987.799     1924000.771      184576.775
      1923998.14      184134.357
#Sta/Elev= 30
       0 2247.53    19.6 2240.12    29.4 2239.67    68.7    2223    78.5 2223.01
    98.2 2214.21   127.6 2199.21   166.9  2176.5   176.7 2175.41   186.5 2170.48
   225.8 2145.73   245.4 2142.61   402.3 2138.81   422.1 2138.21   422.3 2138.22
   471.2 2144.28   490.9 2149.57   520.4 2160.99   559.7 2183.48   569.6 2183.53
   599.1 2206.46   648.2 2250.24   658.1 2251.38   697.4 2282.76   746.5  2318.7
   756.4 2320.89   766.2 2325.85   795.7 2345.98   844.9 2376.68   854.7 2379.58
#Mann= 3 , 0 , 0
       0      .1       0   402.3    .045       0   422.3      .1       0
Bank Sta=402.3,422.3
XS Rating Curve= 0 ,0
Exp/Cntr=0.3,0.1

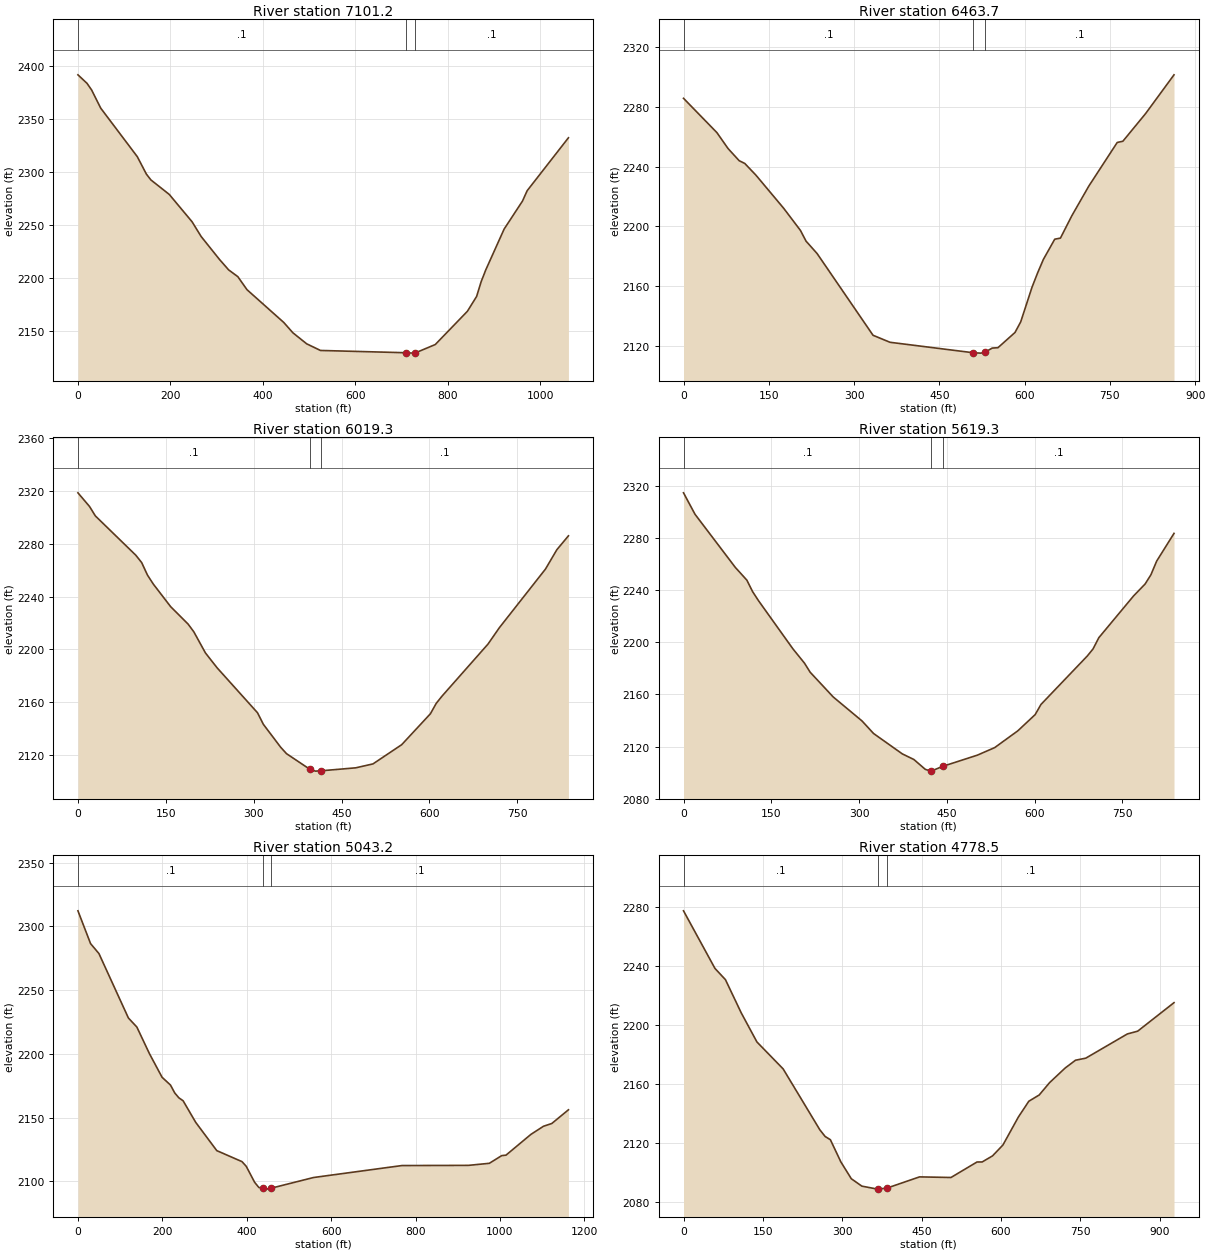
Type RM Length L Ch R = 1 ,7101.2  ,625,637.4,649.9
XS GIS Cut Line= 3
     1924944.192      184737.685     1924710.145      184556.414
     1924100.718      184094.838
#Sta/Elev= 30
       0 2392.02    19.7 2383.94    29.6 2377.69    49.3 2360.52   128.3 2314.73
     148 2298.24   157.9 2292.68   197.4 2279.06   246.7 2253.25   266.4 2239.27
     306 2217.65   325.8 2207.77   345.7 2201.36   365.5 2189.06     445 2158.09
   464.8 2148.31   494.6  2137.9   524.4 2131.64   709.1 2129.49     723 2129.12
   729.1 2129.27   772.6 2137.24   842.1 2168.67     862  2182.7   871.9 2196.76
   881.8 2207.77   921.5 2246.34   961.2  2272.8   971.2 2282.51  1060.5 2332.56
#Mann= 3 , 0 , 0
       0      .1       0   709.1    .045       0   729.1      .1       0
Bank Sta=709.1,729.1
XS Rating Curve= 0 ,0
Exp/Cntr=0.3,0.1

Type RM Length L Ch R = 1 ,6463.7  ,459.8,444.5,431.9
XS GIS Cut Line= 3
     1925099.975      184342.799     1924931.763      184078.377
       1924704.6      183578.159
#Sta/Elev= 30
       0 2285.84    58.8 2262.82    78.4 2252.15    97.9 2244.04   107.7 2242.21
   127.3 2234.38   176.3  2212.1   205.7 2197.31   215.5 2190.15     235 2181.81
   333.4 2127.05   363.3 2122.35     510 2115.33   523.2 2115.09     530 2115.65
   543.1 2118.48   553.1 2118.72   583.1 2128.93   593.1    2136     613 2159.21
     623 2168.96     633 2177.87     653 2191.44     663 2192.15     683 2207.09
   712.9 2226.99   762.9 2256.24   772.9 2257.08   812.8 2275.59   862.8 2301.57
#Mann= 3 , 0 , 0
       0      .1       0     510    .045       0     530      .1       0
Bank Sta=510,530
XS Rating Curve= 0 ,0
Exp/Cntr=0.3,0.1

Type RM Length L Ch R = 1 ,6019.3  ,397.1,399.9,398.9
XS GIS Cut Line= 3
     1925563.093      183861.689     1925215.323      183653.029
      1924870.68      183392.897
#Sta/Elev= 30
       0 2318.47    19.8 2308.14    29.7 2301.03    98.9 2271.23   108.8 2265.72
   118.7 2256.26   128.6 2249.49   158.3 2232.35     188 2219.22   197.8 2213.37
   217.6 2197.42   237.4 2186.21   306.6  2152.1   316.5  2143.4   346.2 2125.98
   356.1 2121.16   395.6 2109.46   405.6 2107.96   415.6 2108.22   474.3 2110.46
   503.7 2113.42   552.8 2127.98   601.8 2151.38   611.6 2159.16   621.5 2164.65
     700 2204.02   719.6 2216.52   798.1 2260.74   817.7 2275.48   837.4 2285.94
#Mann= 3 , 0 , 0
       0      .1       0   395.6    .045       0   415.6      .1       0
Bank Sta=395.6,415.6
XS Rating Curve= 0 ,0
Exp/Cntr=0.3,0.1

Type RM Length L Ch R = 1 ,5619.3  ,553.2,576,599.8
XS GIS Cut Line= 3
     1925701.602      183546.703     1925356.982      183284.428
     1925023.762      183053.634
#Sta/Elev= 30
       0 2314.98    19.7 2298.48    88.6 2257.64   108.3 2247.86   118.1 2239.06
     128 2232.21     187 2195.08   206.7 2184.13   216.5 2177.11   255.9  2158.1
   305.1 2139.68   324.8 2130.05     374 2114.36   393.7 2110.06   413.4 2102.44
   423.1 2101.11   443.1 2104.78   502.3 2113.39   531.9 2119.18   571.5  2132.1
   601.1 2144.56     611 2152.35   690.1 2189.54     700 2195.01   709.9 2203.65
   769.2  2235.7     789 2244.91   798.9 2251.98   808.8 2262.54   838.4  2283.8
#Mann= 3 , 0 , 0
       0      .1       0   423.1    .045       0   443.1      .1       0
Bank Sta=423.1,443.1
XS Rating Curve= 0 ,0
Exp/Cntr=0.3,0.1

Type RM Length L Ch R = 1 ,5043.2  ,265.1,264.7,264.4
XS GIS Cut Line= 3
     1925860.111      183525.001      1925850.55      182757.465
      1925850.55      182362.798
#Sta/Elev= 30
       0 2312.15    29.9 2286.46    49.8 2278.62   119.6 2228.11   139.6 2221.04
   169.5 2200.12   199.4 2181.64   219.3 2175.55   229.3  2169.4   239.2 2165.52
   249.2 2163.24   279.1  2146.3     329 2124.14   388.8  2115.5   398.8 2111.84
   418.7 2099.31   428.7 2095.24   438.6 2094.78   448.6 2093.95   458.6 2094.74
   558.2 2103.05   767.6 2112.43   925.5 2112.58   974.8 2114.19  1004.4 2120.25
  1014.3 2120.57  1073.5  2136.9  1103.1 2143.22  1122.8 2145.39  1162.3 2156.14
#Mann= 3 , 0 , 0
       0      .1       0   438.6    .045       0   458.6      .1       0
Bank Sta=438.6,458.6
XS Rating Curve= 0 ,0
Exp/Cntr=0.3,0.1

Type RM Length L Ch R = 1 ,4778.5  ,368.7,359,348
XS GIS Cut Line= 3
     1926125.899      183464.195     1926111.641      182948.735
     1926070.871      182539.054
#Sta/Elev= 30
       0 2277.71    59.5 2238.64    79.3 2231.04   109.1 2208.55   138.8  2188.8
   188.4 2170.51   257.8 2129.22   267.8  2124.7   277.7 2122.51   297.5 2107.48
   317.3 2096.04   337.2 2091.04   366.9 2089.01   384.9 2089.73   446.2 2097.31
   505.7  2096.9   554.9  2107.4   564.7 2107.43   584.3 2111.56   603.9 2118.91
   633.3 2137.99   652.9  2148.6   672.5 2152.83   692.1  2161.2   721.5 2171.09
   741.1  2176.4   760.7 2177.83   839.1 2194.21   858.7 2196.11   927.4 2215.44
#Mann= 3 , 0 , 0
       0      .1       0   366.9    .045       0   384.9      .1       0
Bank Sta=366.9,384.9
XS Rating Curve= 0 ,0
Exp/Cntr=0.3,0.1

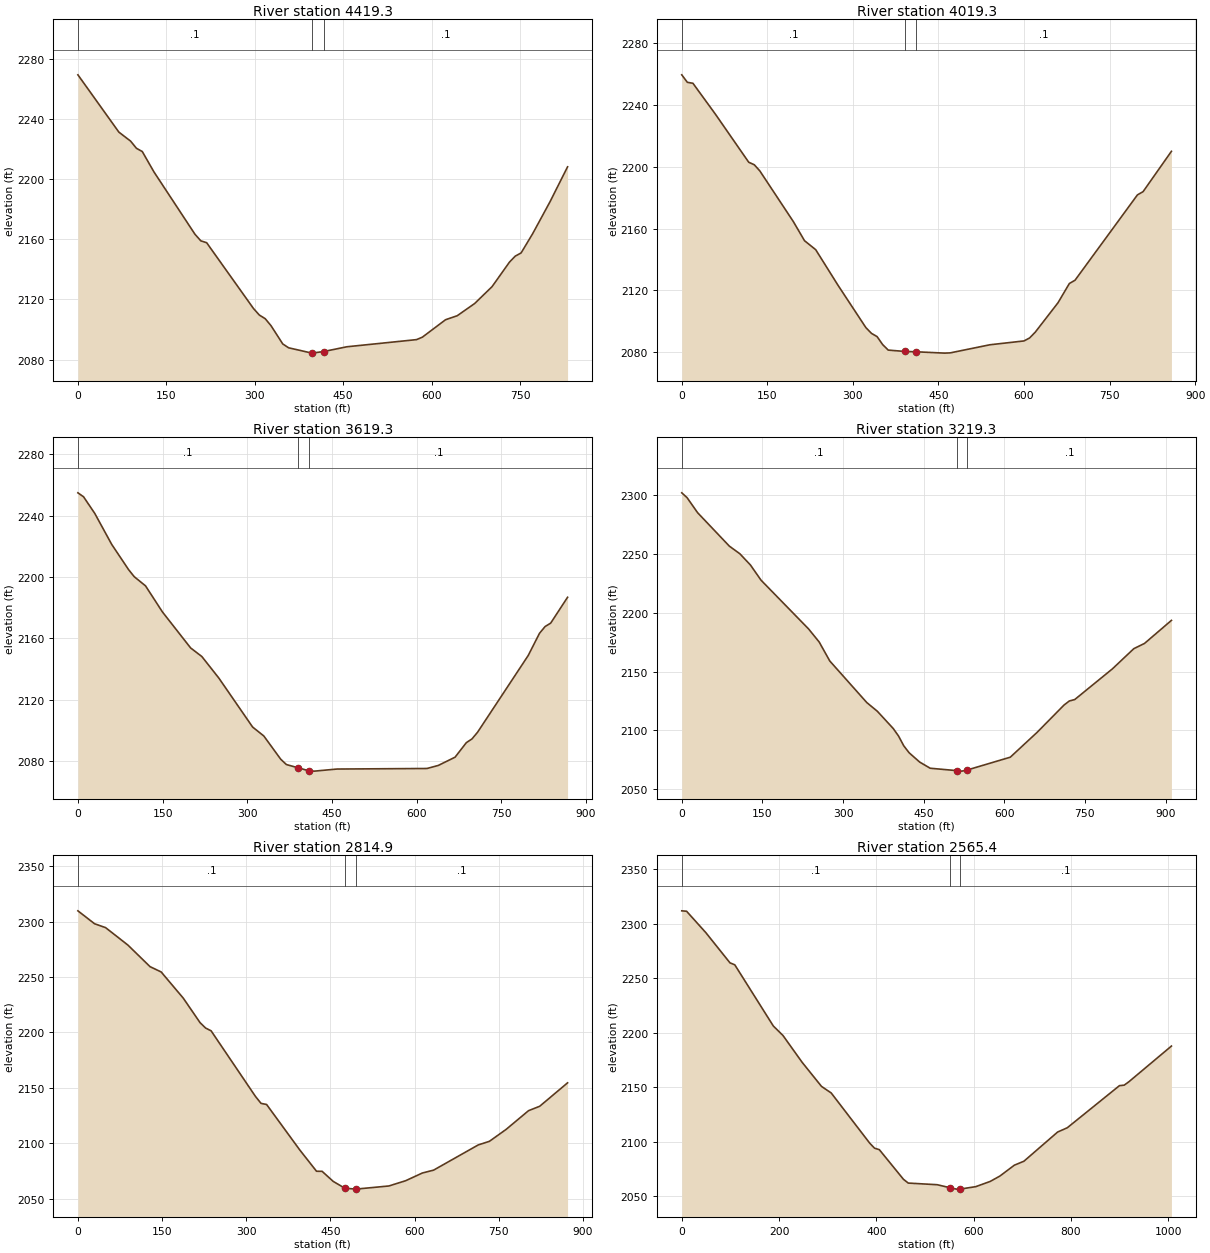
Type RM Length L Ch R = 1 ,4419.3  ,399.7,399.9,396.8
XS GIS Cut Line= 3
     1926629.681      183388.523     1926466.651      183015.581
     1926276.831       182636.94
#Sta/Elev= 30
       0 2269.17    69.5 2231.12    89.4 2225.15    99.3 2220.38   109.2 2218.23
     129  2204.7   198.6 2163.28   208.5 2158.92   218.4 2157.68   297.8    2114
   307.8 2109.62   317.7 2107.23   327.6 2102.56   347.5 2090.45   357.4 2087.89
     397 2084.35     417 2085.42   456.3 2088.57   574.5 2093.32   584.3 2094.95
   623.7 2106.54   643.4 2109.18     673 2117.29   702.5 2128.49   732.1 2144.81
   741.9 2148.77   751.8 2150.89   771.5 2163.74     801    2185   830.6 2208.07
#Mann= 3 , 0 , 0
       0      .1       0     397    .045       0     417      .1       0
Bank Sta=397,417
XS Rating Curve= 0 ,0
Exp/Cntr=0.3,0.1

Type RM Length L Ch R = 1 ,4019.3  ,399.1,399.6,396.5
XS GIS Cut Line= 3
     1926979.974      183217.712     1926811.087      182853.955
     1926546.256      182481.049
#Sta/Elev= 30
       0 2259.53     9.8 2254.68    19.6 2254.05    58.7  2234.2   117.4 2202.93
   127.2 2201.28   136.9  2197.3   195.6  2164.5   215.2 2152.12   234.8 2146.31
   273.9 2123.27   322.8 2095.83   332.6 2092.11   342.4 2090.03   352.1 2084.89
   361.9  2081.3   391.1 2080.41   411.1  2080.2   460.7 2079.33   470.6 2079.49
   540.2 2084.74   599.9 2087.22   609.8 2089.15   619.8 2092.96   659.6 2111.97
   679.5 2124.42   689.4 2126.53   798.8 2181.79   808.7 2183.88   858.4 2210.01
#Mann= 3 , 0 , 0
       0      .1       0   391.1    .045       0   411.1      .1       0
Bank Sta=391.1,411.1
XS Rating Curve= 0 ,0
Exp/Cntr=0.3,0.1

Type RM Length L Ch R = 1 ,3619.3  ,406.8,400.2,402.8
XS GIS Cut Line= 3
     1927243.851      183016.393     1927080.198      182652.312
     1926763.416      182307.778
#Sta/Elev= 30
       0  2254.8      10 2252.22    29.9 2241.37    59.9 2221.17    89.8 2204.71
    99.8 2200.11   119.8 2194.14   149.7 2177.15   199.6 2153.69   219.5 2148.08
   249.5 2134.09   309.4 2102.11   329.3 2096.26   359.2 2081.12   369.2 2077.66
   389.2  2075.6   409.2 2073.56   419.1 2073.36   458.9 2074.72   618.2 2075.08
   638.2 2077.06     668 2082.46     688 2091.95   697.9 2094.34   707.9 2098.76
   797.5 2148.73   817.4 2163.15   827.4 2167.62   837.3 2169.85   867.2  2186.7
#Mann= 3 , 0 , 0
       0      .1       0   389.2    .045       0   409.2      .1       0
Bank Sta=389.2,409.2
XS Rating Curve= 0 ,0
Exp/Cntr=0.3,0.1

Type RM Length L Ch R = 1 ,3219.3  ,389.8,404.4,418.1
XS GIS Cut Line= 3
     1927554.872      182707.716     1927220.973      182307.478
     1926985.393      181996.941
#Sta/Elev= 30
       0 2301.52     9.8 2297.47    29.5 2284.66    88.5 2256.34   108.2  2249.8
   127.8 2240.31   147.5 2227.45     236 2186.09   255.7 2175.01   275.4 2158.93
   344.2 2123.71   363.9 2116.29   393.4 2101.69   403.2 2095.39     413 2087.04
   422.9 2081.15   442.6 2073.24   462.2    2068   511.2 2065.98   521.2 2065.55
   531.2 2066.53   611.2 2077.36   661.2 2098.47   711.1 2121.54   721.1 2125.04
   731.1 2126.24   801.1 2152.22     841 2169.38     861 2173.85     911 2193.37
#Mann= 3 , 0 , 0
       0      .1       0   511.2    .045       0   531.2      .1       0
Bank Sta=511.2,531.2
XS Rating Curve= 0 ,0
Exp/Cntr=0.3,0.1

Type RM Length L Ch R = 1 ,2814.9  ,242.9,249.5,255.8
XS GIS Cut Line= 3
      1927657.72      182671.929     1927601.344      182200.552
     1927560.609      181804.655
#Sta/Elev= 30
       0  2309.9    29.7 2298.23    49.4  2294.7      89 2279.02   128.6 2259.46
   148.4 2254.68   187.9 2230.95   217.6 2208.97   227.5 2204.05   237.4 2201.49
   316.5  2142.2   326.4 2135.95   336.3 2134.95   395.6 2093.76   425.3 2074.62
   435.2 2074.58     455 2065.48   475.5 2059.38   494.6 2058.48   495.5 2058.49
   554.3 2061.33   584.2 2066.09     614 2073.06   633.9 2075.62   713.5 2098.41
   733.4 2101.66   763.3 2112.48   803.1 2129.34     823 2133.32   872.7 2154.49
#Mann= 3 , 0 , 0
       0      .1       0   475.5    .045       0   495.5      .1       0
Bank Sta=475.5,495.5
XS Rating Curve= 0 ,0
Exp/Cntr=0.3,0.1

Type RM Length L Ch R = 1 ,2565.4  ,671.6,682.8,694
XS GIS Cut Line= 3
     1927764.227      182739.109      1927885.84      181936.007
     1928007.452      181784.565
#Sta/Elev= 30
       0 2311.88     9.9  2311.5    49.5 2291.85    99.1 2264.16     109 2262.34
   188.2 2206.22     208 2197.53   247.6 2172.78   287.3 2150.76   307.1  2144.8
   386.3 2098.74   396.2 2094.13   406.1 2092.75   455.7 2065.55   465.6 2062.09
     525 2060.59   552.3 2057.73   564.6 2056.54   572.3 2056.61   604.2  2058.8
     634  2063.6   653.8 2068.51   683.5 2078.47   703.3 2082.14   772.6 2108.92
   792.4 2112.83   899.7 2151.49   909.4 2151.93   919.1 2155.07  1006.5  2187.8
#Mann= 3 , 0 , 0
       0      .1       0   552.3    .045       0   572.3      .1       0
Bank Sta=552.3,572.3
XS Rating Curve= 0 ,0
Exp/Cntr=0.3,0.1

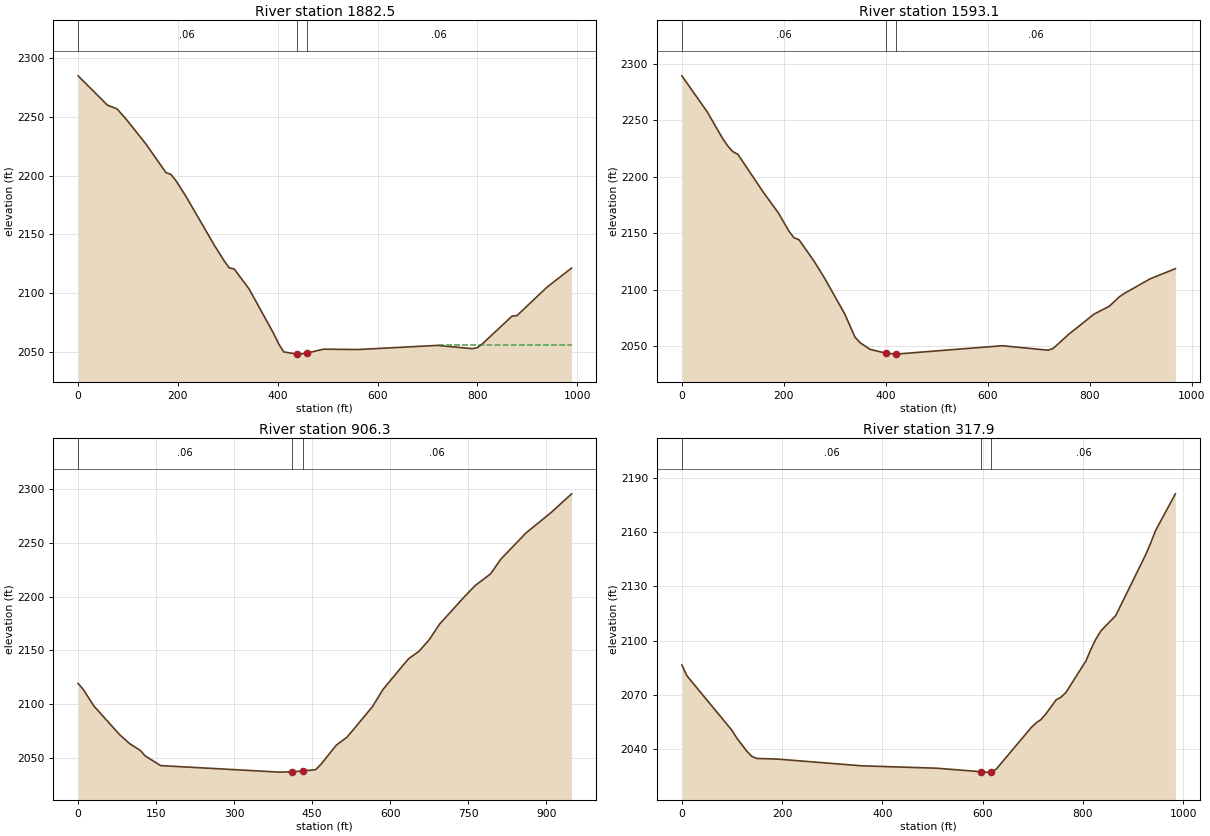
Type RM Length L Ch R = 1 ,1882.5  ,288.1,289.4,290.7
XS GIS Cut Line= 3
     1928060.228      182980.039     1928255.267      182723.047
     1928626.988      182170.053
#Sta/Elev= 30
       0 2285.14    58.7 2260.21    78.2 2256.92    97.8 2247.45   136.9  2226.5
     176 2202.68   185.8 2201.18   195.5 2196.21   215.1 2183.16   273.7 2140.33
   293.3 2127.07   303.1 2121.44   312.8 2120.57   342.5 2103.67   392.2 2065.31
   402.2 2056.55   412.1  2049.9   437.7 2048.11     442    2048   457.7  2048.8
   491.7 2052.22   561.3 2051.93   720.4 2055.45     790 2052.65     800 2053.55
   809.9 2056.66   869.6  2080.4   879.5 2080.85   939.2 2104.91   988.9 2121.34
#Mann= 3 , 0 , 0
       0     .06       0   437.7    .045       0   457.7     .06       0
#XS Ineff= 2 , 0
                          720.52         2055.49
Permanent Ineff=
       F       F
Bank Sta=437.7,457.7
XS Rating Curve= 0 ,0
Exp/Cntr=0.3,0.1

Type RM Length L Ch R = 1 ,1593.1  ,681.6,686.4,691.3
XS GIS Cut Line= 2
     1928314.515      183114.321     1928895.454      182339.852
#Sta/Elev= 30
       0 2289.54    49.9 2257.49    79.8 2234.12    89.8 2227.54    99.8 2222.46
   109.8 2220.03   159.7 2186.48   189.6 2167.87   209.6 2152.23   219.6 2146.18
   229.6 2144.38   259.5 2125.23   279.5 2110.63   319.4  2078.7   339.4 2058.17
   349.3  2053.2   369.3 2047.16   399.7 2043.89   419.2 2042.97   419.7 2042.99
   628.8 2050.42   718.6 2046.43   728.6 2048.09   758.5  2060.4   808.4 2078.38
   838.4 2085.38   858.4 2093.84   868.3 2096.82   918.2 2109.61   968.1 2118.68
#Mann= 3 , 0 , 0
       0     .06       0   399.7    .045       0   419.7     .06       0
#XS Ineff= 2 , 0
                          628.85         2050.31
Permanent Ineff=
       F       F
Bank Sta=399.7,419.7
XS Rating Curve= 0 ,0
Exp/Cntr=0.3,0.1

Type RM Length L Ch R = 1 ,906.3   ,585.5,588.4,591.3
XS GIS Cut Line= 3
     1928828.478      183302.353     1929333.718      182796.473
     1929496.633      182628.969
#Sta/Elev= 30
       0 2119.19     9.9 2113.66    29.8 2098.44    79.4 2071.59    99.3 2062.95
   119.2 2056.82   129.1 2051.48   158.9 2042.52   387.3 2036.44   411.9 2036.77
   431.9 2037.54   456.8 2038.77   466.7 2043.65   496.5 2061.68   516.4 2068.82
   526.3 2074.42     566 2097.62   585.9 2113.42   625.6 2136.63   635.5 2142.24
   655.4 2149.21   675.2 2160.09   695.1 2174.62   744.2 2200.85   763.6 2210.57
   792.9 2221.32   812.3 2234.86     861 2259.51   909.7 2278.72   948.6 2295.96
#Mann= 3 , 0 , 0
       0     .06       0   411.9    .045       0   431.9     .06       0
Bank Sta=411.9,431.9
XS Rating Curve= 0 ,0
Exp/Cntr=0.3,0.1

Type RM Length L Ch R = 1 ,317.9   ,340.9,317.9,294.8
XS GIS Cut Line= 3
     1929083.609       183787.73     1929636.602      183347.172
     1929838.525      183156.722
#Sta/Elev= 30
       0 2086.48      10 2080.54    99.6 2050.41   109.5 2046.06   129.5 2038.75
   139.4  2035.9   149.4 2034.72   189.2 2034.39   358.5 2030.64   507.9 2029.32
   597.5 2027.35   607.4 2027.14   617.4 2027.21   627.4 2028.85   697.1 2051.89
     707 2054.48   716.9 2056.37   726.9 2059.67   746.7 2067.19   756.6  2068.7
   766.5 2071.41   806.2 2088.76   816.1 2095.24     826 2100.88   835.9 2105.38
   865.6  2113.9   925.1 2147.48     935 2153.87     945 2160.95   984.6 2181.34
#Mann= 3 , 0 , 0
       0     .06       0   597.5    .045       0   617.4     .06       0
#XS Ineff= 2 , 0
                          885.96         2124.91
Permanent Ineff=
       F       F
Bank Sta=597.5,617.4
XS Rating Curve= 0 ,0
Exp/Cntr=0.3,0.1

Chan Stop Cuts=-1
Use User Specified Reach Order=0
Composite Channel Slope=5